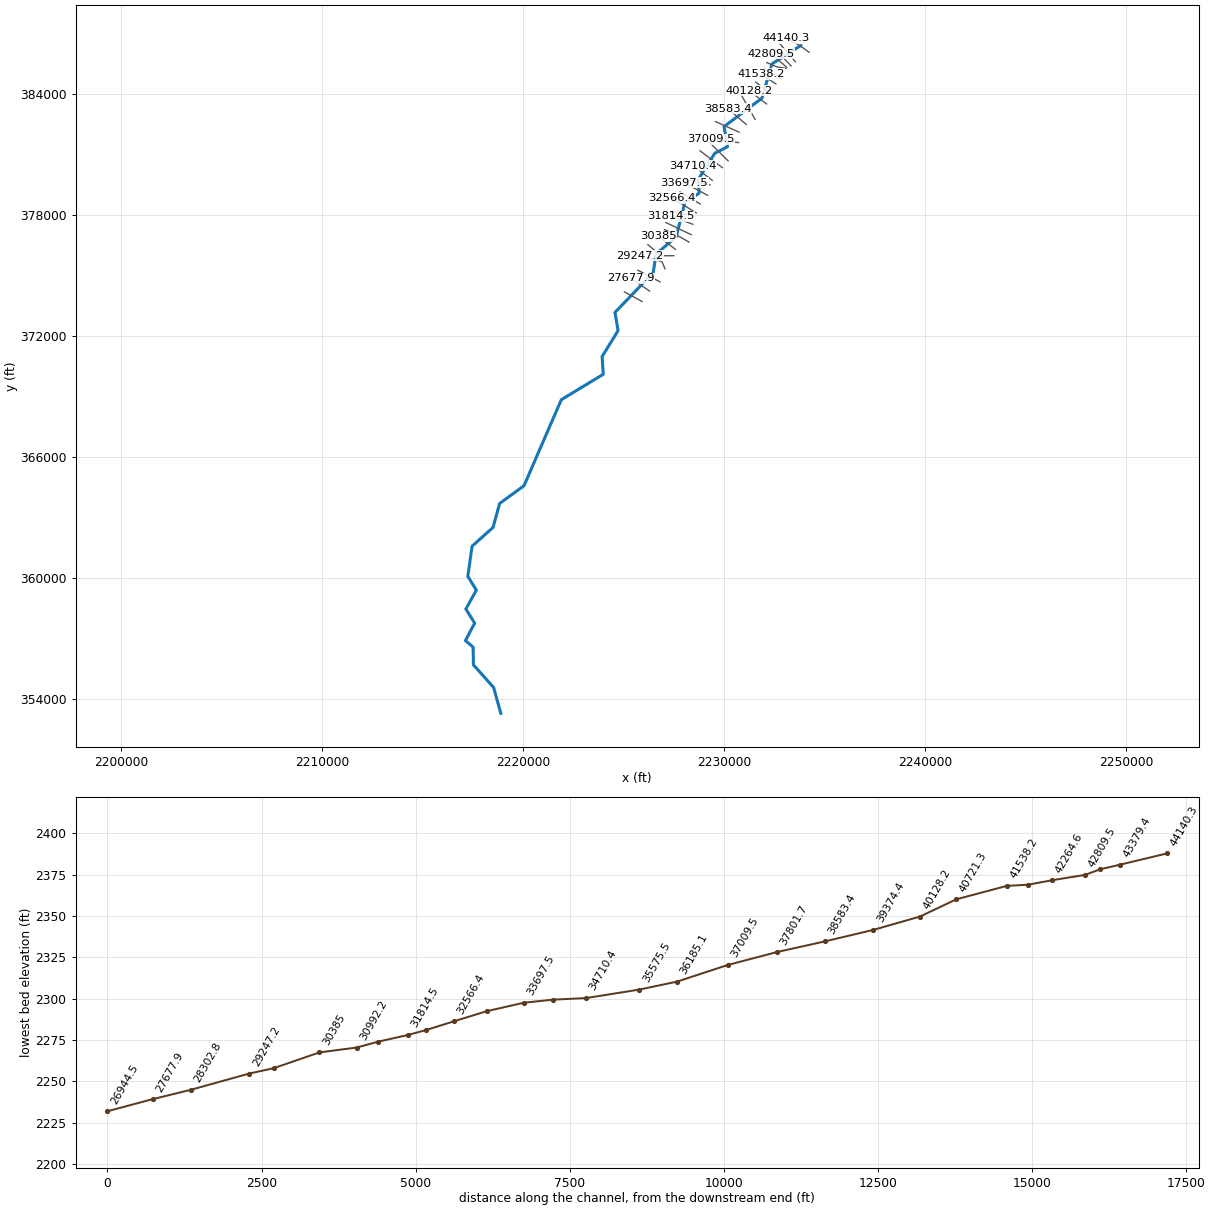
--- NFrkAntCk.prj (project) ---

Proj Title=NFrkAntCk
Current Plan=p01
Default Exp/Contr=0,0
English Units
Geom File=g01
Flow File=f01
Plan File=p01
BEGIN DESCRIPTION:
END DESCRIPTION:
DSS Export Rating Curves= 0
DSS Export Rating Curve Sorted= 0
DSS Export Volume Flow Curves= 0
DXF OffsetX= 0
DXF OffsetY= 0
DXF ScaleX= 0
DXF ScaleY= 0

--- NFrkAntCk.p01 (plan) ---

Plan Title=Floodplain
Program Version=4.00
Geom File=g01
Flow File=f01
K Sum by GR=0
Std Step Tol=0.01
Critical Tol=0.01
Num of Std Step Trials=20
Max Error Tol=0.3
Flow Tol Ratio=0.001
Split Flow NTrial=30
Split Flow Tol=0.02
Split Flow Ratio=0.02
Log Output Level=0
Friction Slope Method=1
Unsteady Friction Slope Method=2
Unsteady Bridges Friction Slope Method=1
Global Log Level=0
CheckData=False
Run HTab=0
Run UNet=0
Run PostProcess=0
UNET Theta=0
UNET Theta Warmup=0
UNET ZTol=0
UNET ZSATol=0
UNET MxIter=0
UNET MaxInSteps=0
UNET DtIC=0
UNET DtMin=0
UNET MaxCRTS=0
UNET WFStab=0
UNET SFStab=0
UNET WFX=0
UNET SFX=0
UNET DSS MLevel=0
UNET DZMax Abort=0
UNET Convert EG Bridges=0
UNET Use Existing IB Tables=0
UNET Froude Limit=0
UNET Froude Power=0
Write IC File=0
Echo Input=False
Echo Output=False
Write Detailed=0

--- NFrkAntCk.f01 (steady flow) ---

Flow Title=NFF Regression Equation
Program Version=4.00
Number of Profiles=1
Profile Names=P100yr
River Rch & RM=NFrkAntCk,Main      ,44140.3
1382.934
River Rch & RM=NFrkAntCk,Main      ,41883.8
1413.581
River Rch & RM=NFrkAntCk,Main      ,41538.2
1570.710
River Rch & RM=NFrkAntCk,Main      ,38583.4
1650.121
River Rch & RM=NFrkAntCk,Main      ,35575.5
1825.815
River Rch & RM=NFrkAntCk,Main      ,34182.1
2020.946
River Rch & RM=NFrkAntCk,Main      ,29247.2
2231.582
River Rch & RM=NFrkAntCk,Main      ,24700
2445.771
River Rch & RM=NFrkAntCk,Main      ,19908.5
2707.451
River Rch & RM=NFrkAntCk,Main      ,11710.7
2850.100
River Rch & RM=NFrkAntCk,Main      ,11277.7
3172.359
River Rch & RM=NFrkAntCk,Main      ,8687
3206.484
River Rch & RM=NFrkAntCk,Main      ,37.6
3562.147
Boundary for River Rch & Prof#=NFrkAntCk,Main      ,1
Up Type=0
Dn Type=3
Dn Slope=0.005413

--- NFrkAntCk.g01 (geometry) ---

Geom Title=USGS 10m DEM
Program Version=4.10

River Reach=NFrkAntCk       ,Main
Reach XY= 30
     2233817.084      386383.582     2232379.584      385471.081
     2231887.396      383774.207     2230002.053      382369.375
     2230172.749      381367.729     2229538.114      381043.655
     2228720.185      379751.252     2228762.136      379064.868
     2228052.148      378608.925     2227621.511       376901.42
     2226621.384      376052.012     2226474.018       375123.13
     2224574.636      373156.628     2224728.282       372251.68
     2223935.495      370969.608     2223989.994      370086.789
     2221904.139      368827.501     2220048.594       364564.18
     2218835.052      363685.274     2218507.246      362496.801
     2217465.764      361568.078     2217251.927      360068.969
     2217676.701      359388.391     2217156.389      358452.453
     2217592.327      357750.891     2217132.951      356886.828
     2217517.326      356561.828     2217531.389      355685.266
     2218537.639      354558.703      2218893.36      353277.844

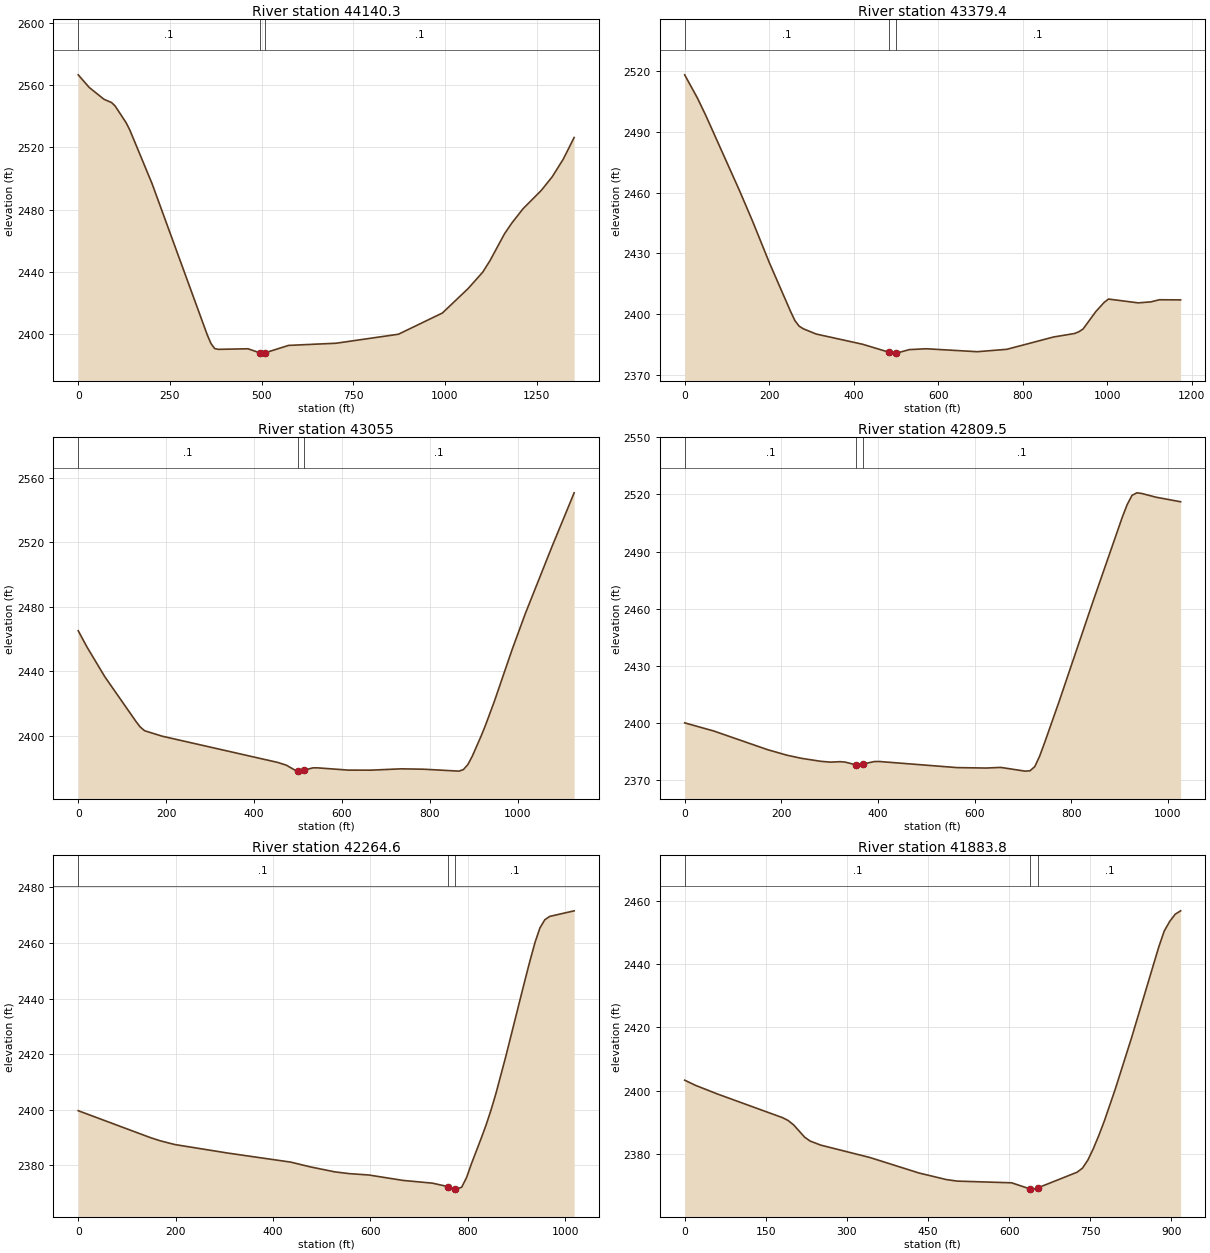
Type RM Length L Ch R = 1 ,44140.3 ,765.6,760.8,758.2
XS GIS Cut Line= 3
     2234234.823      386050.475     2233735.644      386407.756
     2233076.829      386742.231
#Sta/Elev= 30
       0  2566.7    30.2 2558.55    70.4 2550.96    90.6 2548.93   100.6  2546.7
   130.8 2535.86   140.9 2531.14   201.3 2496.82   352.2 2399.37   362.3 2393.86
   372.3 2390.67   382.4 2390.18   462.9 2390.55     495 2387.98   503.2 2387.75
     510 2387.97   573.6 2392.71   703.7 2394.12   873.5  2399.9   993.3 2413.54
  1063.2  2429.2  1103.1 2439.74  1123.1  2447.2    1163 2464.58    1183 2471.48
  1212.9 2480.49  1262.9 2492.34  1292.8 2501.11  1322.8  2512.4  1352.7 2526.39
#Mann= 3 , 0 , 0
       0      .1       0     495    .045       0     510      .1       0
Bank Sta=495,510
XS Rating Curve= 0 ,0
Exp/Cntr=0.3,0.1

Type RM Length L Ch R = 1 ,43379.4 ,323,324.4,325.7
XS GIS Cut Line= 2
     2233551.157       385578.45     2232784.401      386467.571
#Sta/Elev= 30
       0 2517.93    30.1 2506.54    50.2 2497.85   130.4 2460.66   160.6 2445.97
   200.7 2425.36   250.9 2401.39   260.9    2397   270.9 2394.26     281 2392.93
   311.1 2390.38   421.5 2385.32   484.2 2381.38   499.2 2380.98   501.7 2380.97
   531.8  2382.7     572 2383.12   692.4 2381.67   762.6 2382.84     873  2388.9
   923.2 2390.63   933.2 2391.49   943.3 2392.87   973.4 2401.44   993.4    2406
  1003.5 2407.58  1073.7  2405.7  1103.8  2406.2  1123.9 2407.24  1174.1 2407.17
#Mann= 3 , 0 , 0
       0      .1       0   484.2    .045       0   499.2      .1       0
Bank Sta=484.2,499.2
XS Rating Curve= 0 ,0
Exp/Cntr=0.3,0.1

Type RM Length L Ch R = 1 ,43055   ,243.6,245.5,247.4
XS GIS Cut Line= 2
     2233337.783      385374.775      2232552.18      386184.625
#Sta/Elev= 30
       0  2465.2    20.2 2454.99    60.4 2436.73     131 2409.12     141 2405.54
   151.1  2403.2   191.4  2399.8   453.3  2383.6   473.5 2381.87   493.6 2378.72
   499.4 2378.46   503.7 2378.26   514.4 2378.76   533.9 2380.19     544 2380.21
   614.5  2378.8   664.9 2378.76   735.4 2379.59   785.8 2379.35   866.4 2378.17
   876.4 2379.15   886.5 2382.23   896.6 2387.45   916.7 2399.95   926.8 2406.76
     947  2421.6   987.2 2453.55  1017.5 2476.01  1077.9 2517.35  1128.3 2550.66
#Mann= 3 , 0 , 0
       0      .1       0   499.4    .045       0   514.4      .1       0
Bank Sta=499.4,514.4
XS Rating Curve= 0 ,0
Exp/Cntr=0.3,0.1

Type RM Length L Ch R = 1 ,42809.5 ,536.3,544.6,552.9
XS GIS Cut Line= 2
     2233113.966       385311.16      2232342.96      385989.181
#Sta/Elev= 30
       0 2400.12    60.4 2395.83   171.1 2386.09   211.4 2383.16   241.6 2381.51
   281.8 2379.93     302  2379.5   322.1 2379.74   332.2 2379.52   354.4 2378.09
   369.4 2378.51   392.6  2379.8   402.6 2379.84   563.7 2376.63   624.1  2376.4
   654.3 2376.73   704.6 2374.78   714.7 2374.93   724.8 2377.16   734.8 2382.62
   744.9 2389.54   775.1 2411.28   845.5 2463.97   905.9 2508.04     916 2514.65
   926.1 2519.52   936.1 2520.86   946.2 2520.52   976.4 2518.53  1026.7 2516.17
#Mann= 3 , 0 , 0
       0      .1       0   354.4    .045       0   369.4      .1       0
Bank Sta=354.4,369.4
XS Rating Curve= 0 ,0
Exp/Cntr=0.3,0.1

Type RM Length L Ch R = 1 ,42264.6 ,385,380.2,375.3
XS GIS Cut Line= 3
     2233095.313       385253.54      2232634.62      385326.281
     2232125.433      385539.655
#Sta/Elev= 30
       0  2399.7   148.8 2389.98   168.7 2388.86   198.5 2387.52   307.6 2384.45
   436.6  2381.2   476.4  2379.5   526.6 2377.71   556.7 2377.06   596.9 2376.57
   667.2 2374.62   727.4 2373.64   759.6 2372.38   774.6 2371.61   777.6 2371.49
   787.6 2372.21   797.6 2375.67   807.7  2380.7   827.8 2389.86   837.8 2394.64
   847.8 2399.95   857.9  2405.9     878 2419.13   918.1 2447.07   928.2 2453.88
   938.2 2460.26   948.2 2465.42   958.3 2468.38   968.3 2469.57  1018.5 2471.58
#Mann= 3 , 0 , 0
       0      .1       0   759.6    .045       0   774.6      .1       0
Bank Sta=759.6,774.6
XS Rating Curve= 0 ,0
Exp/Cntr=0.3,0.1

Type RM Length L Ch R = 1 ,41883.8 ,345.7,345.7,345.7
XS GIS Cut Line= 2
     2232784.952      384749.202     2232018.746       385253.54
#Sta/Elev= 30
       0 2403.31    20.2 2401.67    60.5 2398.95   181.4 2391.43   191.5 2390.54
   201.6 2389.15   221.8  2385.3   231.8 2384.07     252 2382.75   342.7 2378.84
   433.4 2373.94   483.8 2371.87     504 2371.38   604.8 2370.84   638.7  2368.9
   645.1 2368.84   653.7 2369.28   725.8 2374.19   735.8 2375.48   745.9 2378.08
     756 2381.71   766.1 2385.86   776.2  2390.4   796.3 2400.42   826.6 2416.76
     877 2445.53     887 2450.51   897.1 2453.54   907.2 2455.82   917.3  2456.9
#Mann= 3 , 0 , 0
       0      .1       0   638.7    .045       0   653.7      .1       0
Bank Sta=638.7,653.7
XS Rating Curve= 0 ,0
Exp/Cntr=0.3,0.1

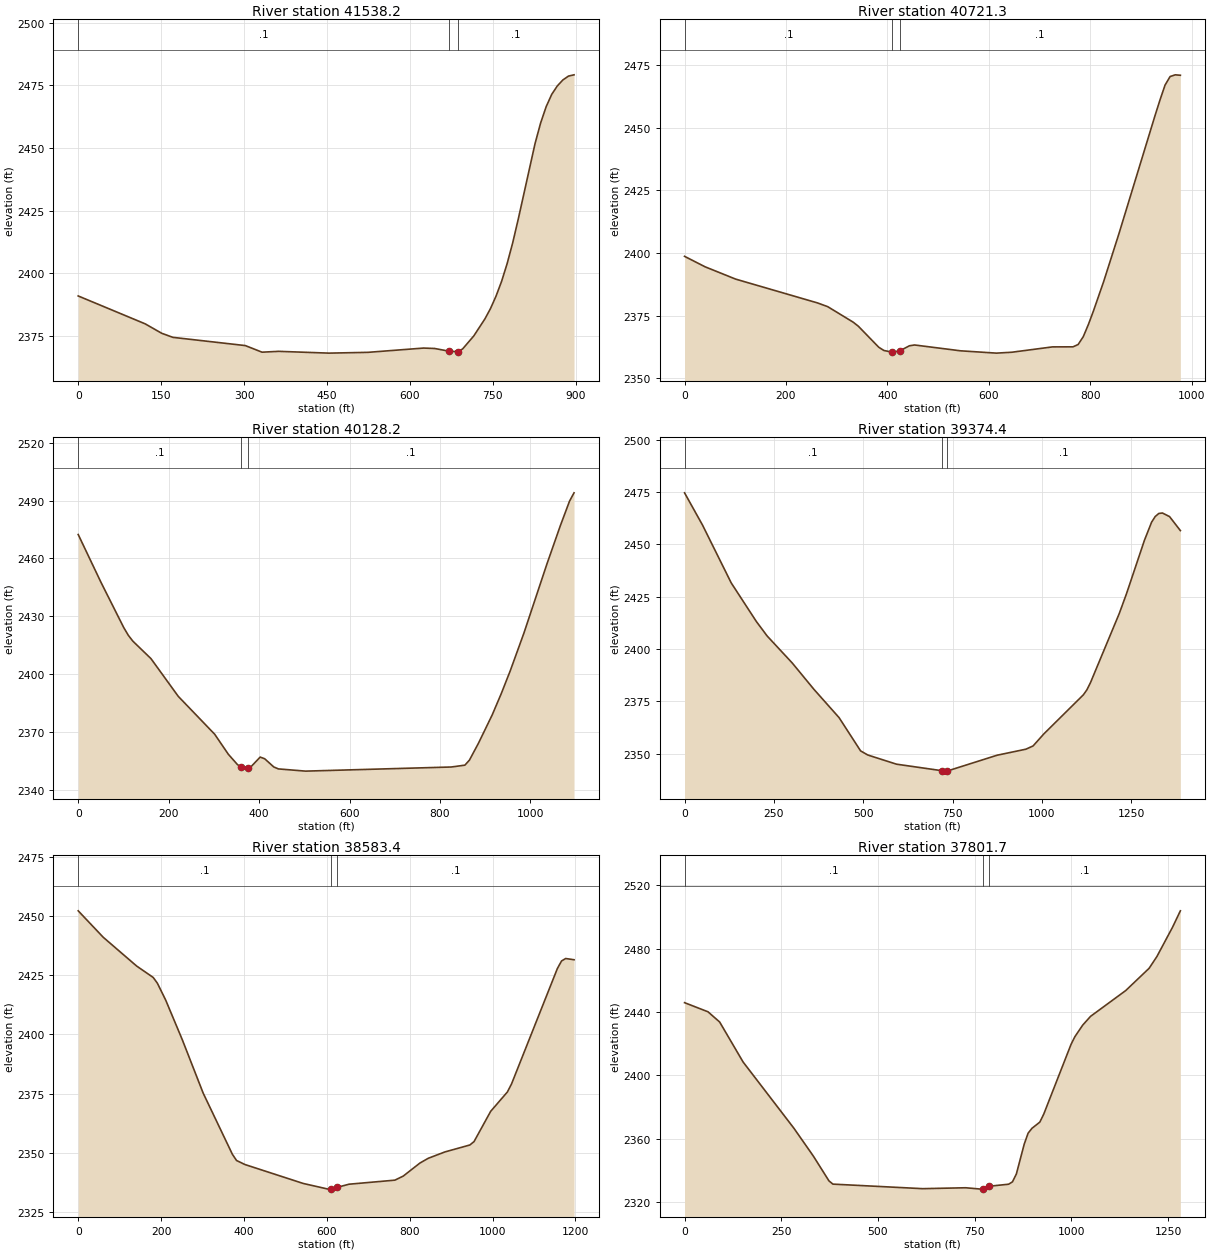
Type RM Length L Ch R = 1 ,41538.2 ,818.4,816.9,814
XS GIS Cut Line= 2
     2232581.277      384482.485     2231829.619      384972.275
#Sta/Elev= 30
       0 2390.94     121 2379.83   151.2 2376.04   171.4 2374.42   302.4 2371.14
   332.6 2368.51   362.9 2368.84   453.6 2368.13   524.2 2368.44     625 2370.15
   645.1 2369.98   671.5 2368.88   686.5 2368.72   695.6  2369.8   715.7 2374.96
   735.9 2381.77     746 2385.89     756 2390.84   766.1 2396.75   776.2 2403.88
   786.3  2412.2   796.4 2421.72   826.6 2451.67   836.7 2459.91   846.8 2466.46
   856.8 2471.35   866.9 2474.71     877 2477.11   887.1 2478.65   897.2 2479.16
#Mann= 3 , 0 , 0
       0      .1       0   671.5    .045       0   686.5      .1       0
Bank Sta=671.5,686.5
XS Rating Curve= 0 ,0
Exp/Cntr=0.3,0.1

Type RM Length L Ch R = 1 ,40721.3 ,594.3,593.1,593.2
XS GIS Cut Line= 2
     2232348.505      383973.298      2231577.45      384574.624
#Sta/Elev= 30
       0 2398.66    40.3  2394.5   100.8 2389.57   262.1 2380.08   282.3 2378.59
   332.7 2372.38   342.7 2370.79   383.1 2362.38   393.1 2361.11     410  2360.4
     425 2361.02   443.5 2362.98   453.6  2363.3   544.4 2360.97   614.9 2360.05
   645.2  2360.4   725.8 2362.54   766.1 2362.56   776.2 2363.49   786.3 2366.61
   796.4 2371.46   806.4 2376.88   826.6 2388.64   856.8 2407.78   927.4 2454.51
   937.5 2460.96   947.6 2466.96   957.6 2470.37   967.7 2471.05   977.8 2470.88
#Mann= 3 , 0 , 0
       0      .1       0     410    .045       0     425      .1       0
Bank Sta=410,425
XS Rating Curve= 0 ,0
Exp/Cntr=0.3,0.1

Type RM Length L Ch R = 1 ,40128.2 ,762.9,753.8,744.7
XS GIS Cut Line= 2
     2232115.734      383488.358     2231242.271      384151.063
#Sta/Elev= 30
       0 2472.44    50.3 2447.64   100.6 2424.16   110.6 2420.19   120.7 2417.11
   160.9    2408   221.3 2388.41   301.8 2368.75   331.9 2358.38   352.1 2353.01
   359.5 2351.81   374.5 2351.19   382.2 2351.91   402.4  2356.9   412.4 2356.01
   432.5 2351.76   442.6 2350.75   502.9  2349.6   824.8 2351.74     855 2352.69
   865.1  2355.3   885.2 2364.14   915.4 2378.76   935.5 2389.84   955.6 2401.84
   985.8 2421.39  1036.1 2456.89  1066.2 2477.06  1086.4 2489.72  1096.4 2494.07
#Mann= 3 , 0 , 0
       0      .1       0   359.5    .045       0   374.5      .1       0
Bank Sta=359.5,374.5
XS Rating Curve= 0 ,0
Exp/Cntr=0.3,0.1

Type RM Length L Ch R = 1 ,39374.4 ,783,791,799
XS GIS Cut Line= 2
     2231548.853      382720.067     2230863.917      383927.043
#Sta/Elev= 30
       0 2474.68    50.3 2459.26   130.7 2431.58   201.1 2413.11   231.3 2406.19
   301.7 2393.24     362 2380.72   432.4 2367.19   492.8 2351.25   512.9 2349.28
   593.3 2344.89   719.7 2341.79   734.1 2341.57   734.7 2341.59   874.9 2349.18
   955.4 2352.06   975.5 2353.61  1005.6 2359.36  1116.3 2378.07  1126.3  2380.5
  1136.4 2383.98  1216.8 2416.97  1236.9 2426.37  1287.2 2451.96  1307.3 2460.65
  1317.4 2463.35  1327.4  2464.8  1337.5 2465.03  1357.6  2463.3  1387.8 2456.62
#Mann= 3 , 0 , 0
       0      .1       0   719.7    .045       0   734.7      .1       0
Bank Sta=719.7,734.7
XS Rating Curve= 0 ,0
Exp/Cntr=0.3,0.1

Type RM Length L Ch R = 1 ,38583.4 ,773.7,781.3,788.9
XS GIS Cut Line= 2
     2231102.209      382474.833     2230195.371      383255.586
#Sta/Elev= 30
       0 2452.24    60.3 2441.08   140.8 2428.93     181 2424.07   191.1 2421.64
   211.2 2414.48   251.4 2397.67   301.7 2375.13   372.1 2349.32   382.1  2346.7
   402.2    2345     543 2336.99   603.3 2334.59   610.3 2334.62   625.3 2335.36
   653.6 2336.67   764.2 2338.38   784.4  2340.1   824.6  2345.6   844.7 2347.62
   884.9 2350.31   945.2 2353.25   955.3 2354.69   995.5  2367.5  1035.7 2375.64
  1045.8 2379.07  1156.4 2427.84  1166.5 2431.05  1176.5 2432.08  1196.6 2431.56
#Mann= 3 , 0 , 0
       0      .1       0   610.3    .045       0   625.3      .1       0
Bank Sta=610.3,625.3
XS Rating Curve= 0 ,0
Exp/Cntr=0.3,0.1

Type RM Length L Ch R = 1 ,37801.7 ,787.1,792.1,797.1
XS GIS Cut Line= 2
     2230748.183       382088.84     2229579.497      382615.465
#Sta/Elev= 30
       0 2445.89    60.6 2440.13    90.8 2433.67   151.4 2408.41   282.6 2366.62
   333.1 2348.96   373.4 2333.32   383.6 2331.28   615.7 2328.41   726.7 2328.98
   767.1 2328.12   771.2 2328.43   786.2  2329.9   837.8 2331.22   847.8 2332.72
   857.9  2337.7   878.1 2356.44   888.2 2363.45   898.3 2366.55   918.5 2370.44
   928.6 2375.44   999.2 2419.52  1009.3 2424.46  1029.5 2431.74  1049.7 2437.25
  1140.6 2453.54  1201.1  2467.6  1221.3 2475.06  1261.7 2493.56  1281.9  2503.9
#Mann= 3 , 0 , 0
       0      .1       0   771.2    .045       0   786.2      .1       0
Bank Sta=771.2,786.2
XS Rating Curve= 0 ,0
Exp/Cntr=0.3,0.1

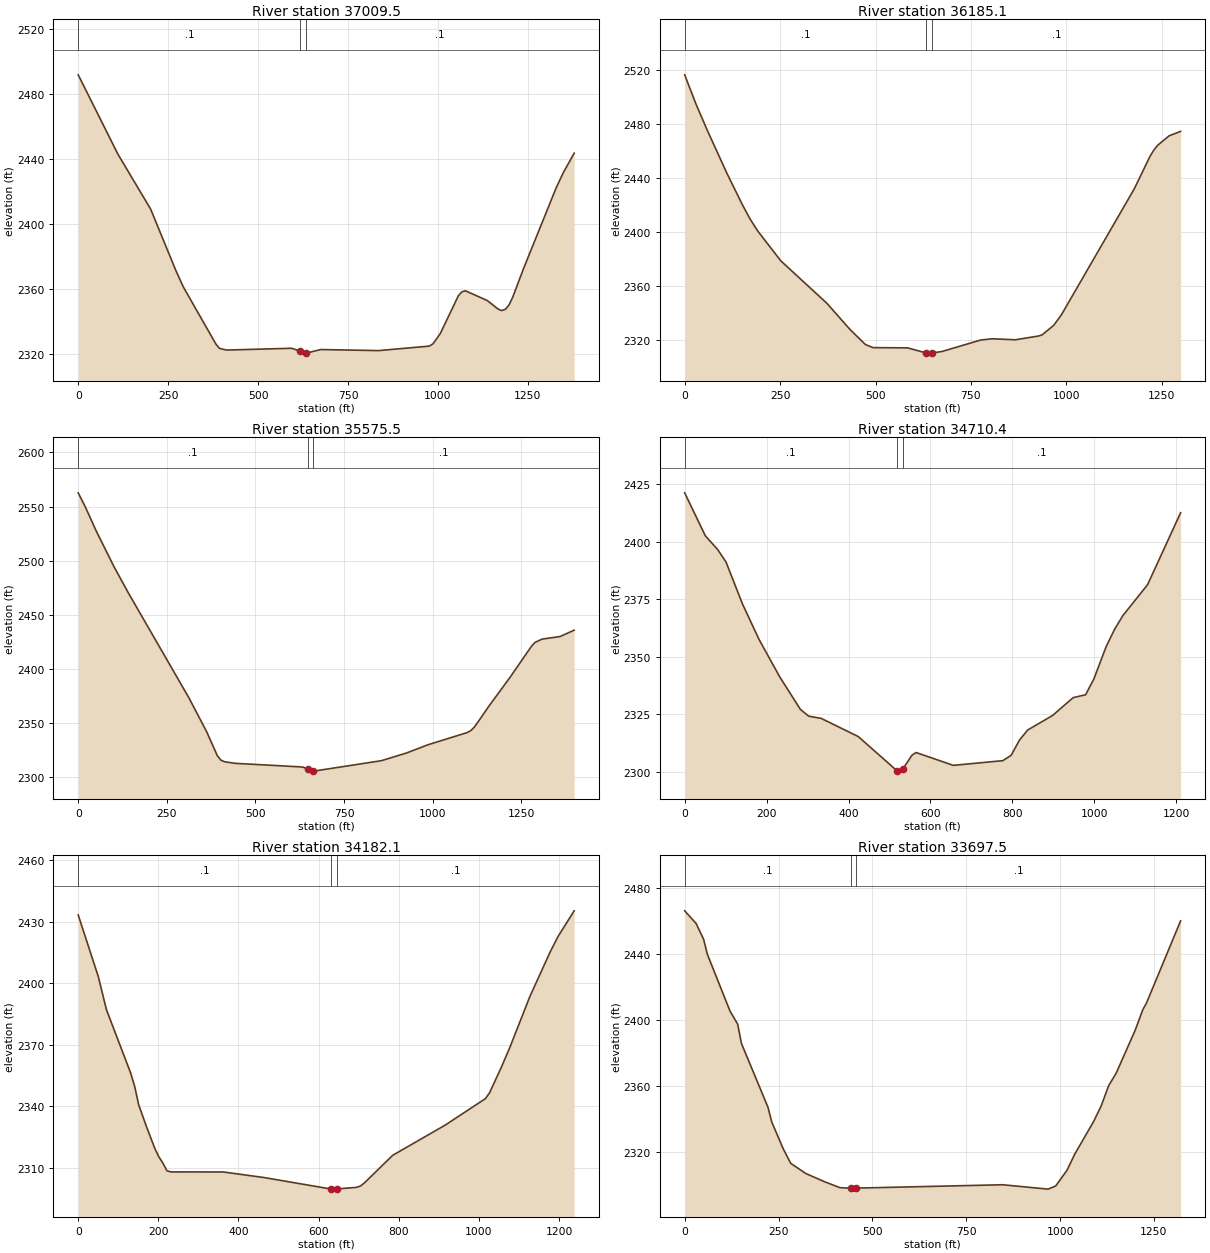
Type RM Length L Ch R = 1 ,37009.5 ,837.4,824.4,811.4
XS GIS Cut Line= 2
     2230723.956      381572.844     2229356.552      381748.135
#Sta/Elev= 30
       0 2491.87   110.7 2442.84   201.2 2409.19   271.7 2371.14   291.8  2361.3
   382.4 2326.09   392.4 2323.32   412.6 2322.25   593.7 2323.36   617.7  2321.5
   632.7 2320.42     634 2320.36   674.2 2322.57   835.2 2321.92   976.1 2324.69
   986.2  2326.1  1006.3 2332.34  1056.6 2355.66  1066.6 2358.16  1076.7 2358.75
  1137.1 2352.77  1167.3  2347.5  1177.3 2346.58  1187.4 2347.36  1197.5 2350.03
  1207.5 2354.63  1237.7 2372.35  1328.3 2422.05  1348.4 2431.57  1378.6 2443.57
#Mann= 3 , 0 , 0
       0      .1       0   617.7    .045       0   632.7      .1       0
Bank Sta=617.7,632.7
XS Rating Curve= 0 ,0
Exp/Cntr=0.3,0.1

Type RM Length L Ch R = 1 ,36185.1 ,608.7,609.6,610.2
XS GIS Cut Line= 2
      2230200.22      380670.855     2229275.554       381583.63
#Sta/Elev= 30
       0 2516.25    30.2 2494.22    60.4  2474.5   110.8 2443.32   151.1 2420.16
   171.2 2409.62   191.4 2400.67   251.8 2378.62   372.7 2347.15   433.1 2327.82
   473.4 2316.68   493.5 2314.37   584.2  2314.2   632.8 2310.41   634.5  2310.3
   647.8 2310.34   674.8 2311.57   775.6    2320   805.8 2320.91   866.2 2320.18
   926.6 2322.94   936.7 2323.87   966.9 2330.89   987.1 2338.71  1178.4 2432.14
  1218.7 2455.72  1228.8 2460.38  1238.9 2464.04  1269.1 2471.11  1299.3 2474.41
#Mann= 3 , 0 , 0
       0      .1       0   632.8    .045       0   647.8      .1       0
Bank Sta=632.8,647.8
XS Rating Curve= 0 ,0
Exp/Cntr=0.3,0.1

Type RM Length L Ch R = 1 ,35575.5 ,865.6,865.1,864.6
XS GIS Cut Line= 2
     2229916.351      380330.866     2228799.347      381172.865
#Sta/Elev= 30
       0 2562.69    20.1 2549.64    50.3  2527.8   100.6 2494.63   140.9 2470.51
     312 2373.39   362.3 2341.92   392.5 2319.69   402.5 2315.66   412.6 2314.19
   442.8 2312.71   623.9 2309.49     634 2309.22   647.3  2307.4   662.3 2305.66
   664.2 2305.51   855.4 2315.17   925.8 2322.25   986.2 2329.84  1096.9 2341.12
    1107 2342.87    1117 2346.14  1127.1 2350.67  1157.3 2365.07  1217.7 2392.06
    1278 2420.72  1288.1 2424.38  1308.2 2427.51  1358.6 2429.85  1398.8 2435.75
#Mann= 3 , 0 , 0
       0      .1       0   647.3    .045       0   662.3      .1       0
Bank Sta=647.3,662.3
XS Rating Curve= 0 ,0
Exp/Cntr=0.3,0.1

Type RM Length L Ch R = 1 ,34710.4 ,518.5,528.2,538
XS GIS Cut Line= 2
     2229414.617      379700.975     2228454.436      380438.084
#Sta/Elev= 30
       0 2421.35    50.4 2402.68    80.7 2396.66   100.9 2391.28   141.2 2373.01
   181.6 2357.59     232 2341.37   282.4 2327.23   302.6 2324.27   332.9 2323.33
   423.7 2315.41   518.3 2300.52   524.5 2300.38   533.3  2301.5   554.8 2307.31
   564.9 2308.46   655.7 2302.89   776.7 2304.93   796.9 2307.27   817.1 2313.85
   837.2 2318.25   897.8 2324.54   948.2 2332.33   978.5 2333.57   998.6 2340.36
  1028.9 2354.56  1049.1 2361.94  1069.3 2367.92  1129.8 2381.41  1210.5  2412.7
#Mann= 3 , 0 , 0
       0      .1       0   518.3    .045       0   533.3      .1       0
Bank Sta=518.3,533.3
XS Rating Curve= 0 ,0
Exp/Cntr=0.3,0.1

Type RM Length L Ch R = 1 ,34182.1 ,492.9,484.7,472.7
XS GIS Cut Line= 2
     2229303.081      379477.902      2228095.58      379749.469
#Sta/Elev= 30
       0 2433.31    50.3 2403.11    70.4  2387.1   130.8 2356.19   140.9 2349.64
   150.9 2340.62   171.1 2329.57   191.2 2319.32   201.2 2315.24   211.3 2312.19
   221.4 2308.41   231.4 2307.85   362.2 2307.82   462.9 2305.13     632 2299.47
   633.9 2299.45     647 2299.56   694.3 2300.31   704.4 2300.96   714.4 2302.51
   784.9 2315.97   915.7 2330.68  1016.3 2343.64  1026.4 2346.39  1056.5 2359.18
  1076.7 2368.38    1127  2393.4  1177.3 2415.02  1197.4 2422.76  1237.7 2435.32
#Mann= 3 , 0 , 0
       0      .1       0     632    .045       0     647      .1       0
Bank Sta=632,647
XS Rating Curve= 0 ,0
Exp/Cntr=0.3,0.1

Type RM Length L Ch R = 1 ,33697.5 ,597.7,599.5,608.1
XS GIS Cut Line= 2
     2229181.846      378959.016     2228017.989      379584.589
#Sta/Elev= 30
       0 2466.31    30.3  2458.7    50.4 2449.13    60.5 2439.94     111  2411.1
     121 2405.45   141.2  2397.6   151.3 2385.86   221.9  2347.2     232 2338.27
   262.2 2322.17   282.4 2313.21   322.8 2307.02   373.2 2301.98   413.5 2298.45
   442.6 2298.08   457.6 2298.17   847.3  2300.2   968.3 2297.55   988.5 2299.47
  1018.7 2309.01  1038.9 2318.61  1089.3 2338.47  1109.5  2347.9  1129.7 2360.32
  1149.9 2367.99  1200.3 2393.92  1220.5 2406.34  1230.6 2410.53  1321.3 2460.22
#Mann= 3 , 0 , 0
       0      .1       0   442.6    .045       0   457.6      .1       0
Bank Sta=442.6,457.6
XS Rating Curve= 0 ,0
Exp/Cntr=0.3,0.1

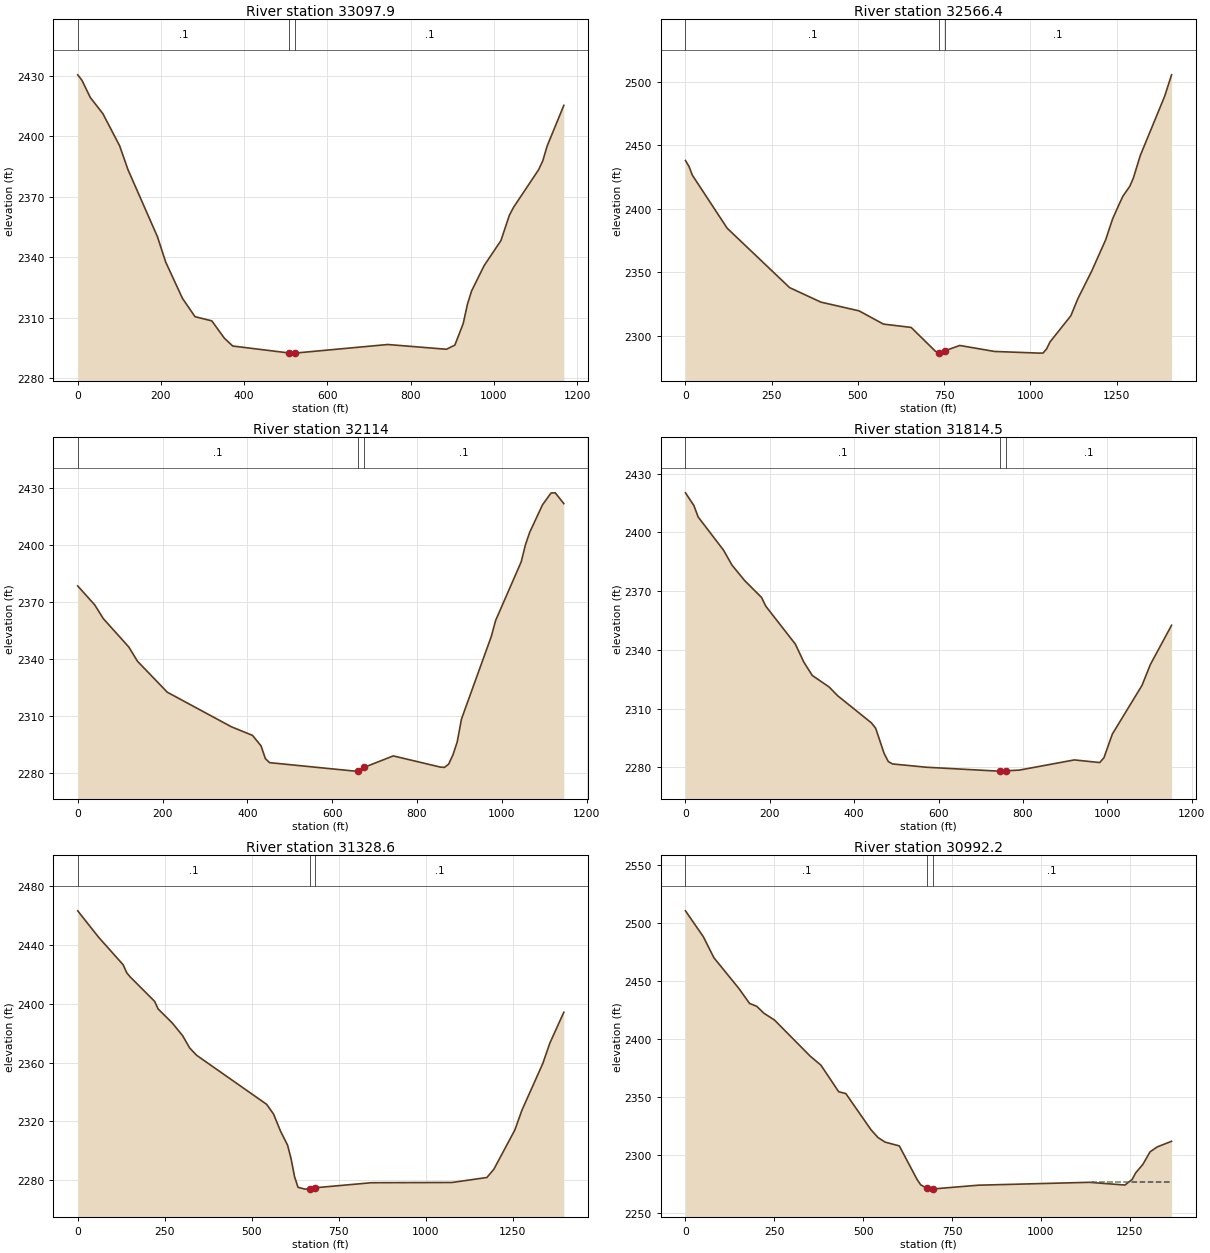
Type RM Length L Ch R = 1 ,33097.9 ,533.6,531.5,526.4
XS GIS Cut Line= 2
     2228813.291      378532.269     2227809.465      379128.745
#Sta/Elev= 30
       0 2430.62    10.1 2427.95    30.2 2419.37    60.4 2411.35   100.7 2395.38
   120.8  2383.5   191.3 2350.36   211.4 2337.64   251.6 2319.64   281.8 2310.54
   322.1 2308.46   352.3 2299.85   372.4 2295.97   507.9 2292.51   513.4 2292.44
   522.9 2292.48   744.9 2296.72   885.8 2294.36     906 2296.44   926.1 2307.16
   936.2 2316.74   946.2 2323.34   976.4 2335.93  1016.7 2348.33  1036.8 2360.84
  1046.9 2364.82  1107.3 2383.54  1117.3 2387.98  1127.4 2395.12  1167.7 2415.45
#Mann= 3 , 0 , 0
       0      .1       0   507.9    .045       0   522.9      .1       0
Bank Sta=507.9,522.9
XS Rating Curve= 0 ,0
Exp/Cntr=0.3,0.1

Type RM Length L Ch R = 1 ,32566.4 ,443.5,452.3,461.1
XS GIS Cut Line= 2
     2228619.315      378086.124     2227421.513      378828.082
#Sta/Elev= 30
       0 2438.13    10.1 2433.51    20.1 2426.52   120.8 2384.81   301.9 2337.98
   392.5 2326.55   503.2 2319.67   573.7 2309.25   654.2 2306.61   724.6 2287.82
   735.9 2286.65   750.9 2288.09   795.1  2292.4   895.7 2287.68  1026.5 2286.36
  1036.6 2286.44  1046.7 2289.67  1056.7 2295.17  1117.1 2315.82  1137.2 2329.12
  1177.5 2350.99  1217.8  2375.5  1237.9 2391.98    1258 2404.22  1268.1 2410.07
  1288.2 2417.94  1298.3 2424.34  1318.4 2442.11  1388.8 2488.59    1409 2505.64
#Mann= 3 , 0 , 0
       0      .1       0   735.9    .045       0   750.9      .1       0
Bank Sta=735.9,750.9
XS Rating Curve= 0 ,0
Exp/Cntr=0.3,0.1

Type RM Length L Ch R = 1 ,32114   ,304.4,299.7,295
XS GIS Cut Line= 2
     2228444.737      377960.039     2227314.826      378154.016
#Sta/Elev= 30
       0 2378.51    40.2 2368.51    60.3 2361.33   120.7 2346.32   140.8 2338.93
   211.2  2322.6     362 2304.45   412.3 2299.86   432.4 2294.34   442.5 2287.69
   452.5 2285.53   653.7 2281.07   660.4 2281.33   675.4 2283.05   744.2 2289.08
   854.8 2283.22   864.9 2283.03   874.9 2284.78     885 2289.66     895 2296.45
   905.1  2308.5   975.5 2352.01   985.5 2360.29  1045.9 2391.19  1055.9 2400.16
    1066 2406.76  1096.2 2421.21  1116.3 2427.42  1126.3  2427.5  1146.4 2421.83
#Mann= 3 , 0 , 0
       0      .1       0   660.4    .045       0   675.4      .1       0
Bank Sta=660.4,675.4
XS Rating Curve= 0 ,0
Exp/Cntr=0.3,0.1

Type RM Length L Ch R = 1 ,31814.5 ,487.3,485.6,483.9
XS GIS Cut Line= 2
     2228449.586      377523.593      2227368.17      377921.244
#Sta/Elev= 30
       0 2420.27      20 2413.78    30.1 2407.92    90.2 2390.99   110.2 2383.35
   140.3 2375.43   180.4 2366.79   190.4 2362.34   260.5 2342.95   280.5 2333.78
   300.6 2326.93   340.6 2321.04   360.7 2316.58   440.8  2302.7   450.9 2299.93
   470.9 2287.06   480.9 2282.91   490.9 2281.71   571.1 2280.03   741.4 2278.04
   744.9 2278.06   759.9 2278.22   791.5 2278.56   921.8 2283.77   981.9 2282.42
   991.9 2284.88  1011.9 2297.01  1082.1 2321.84  1102.1 2332.56  1152.2 2352.58
#Mann= 3 , 0 , 0
       0      .1       0   744.9    .045       0   759.9      .1       0
Bank Sta=744.9,759.9
XS Rating Curve= 0 ,0
Exp/Cntr=0.3,0.1

Type RM Length L Ch R = 1 ,31328.6 ,337.4,336.4,336.9
XS GIS Cut Line= 2
     2228367.146      377009.557     2227106.302      377610.883
#Sta/Elev= 30
       0 2463.34    60.3  2445.3   130.6 2426.63   140.7 2421.24   150.7 2418.38
   221.1 2401.72   231.1 2396.57   271.3 2387.14   301.5 2378.38   321.6 2370.08
   341.7 2365.05   542.7 2331.72   562.8 2325.05   582.9 2313.39     603 2303.93
     613 2294.82   623.1 2282.51   633.1 2275.22   653.2 2273.98   667.1 2274.21
   682.1  2274.9   844.2 2278.34  1075.3  2278.5  1175.8 2281.89  1195.9 2287.51
  1256.2 2314.24  1276.3 2327.55  1336.6 2359.52  1356.7 2373.29  1396.9 2394.33
#Mann= 3 , 0 , 0
       0      .1       0   667.1    .045       0   682.1      .1       0
Bank Sta=667.1,682.1
XS Rating Curve= 0 ,0
Exp/Cntr=0.3,0.1

Type RM Length L Ch R = 1 ,30992.2 ,610.7,607.2,602.2
XS GIS Cut Line= 3
     2228258.797       376643.59     2227664.174      376977.414
     2227040.347      377262.267
#Sta/Elev= 30
       0 2510.34    50.1 2488.12    80.2 2469.84   150.4 2443.41   180.5 2430.52
   200.6 2428.06   220.6 2422.14   250.7 2416.19     351 2385.11   381.1 2377.37
   431.2 2354.44   451.3 2352.85   521.5 2321.92   541.5 2315.04   561.6 2311.06
   601.7 2307.78   651.8  2278.8   661.9 2274.23   680.4  2271.1     692 2270.53
   695.4 2270.64   823.1 2273.91  1135.8  2276.4  1236.6 2274.05  1256.8 2278.84
  1266.8 2284.54    1287 2291.84  1307.2 2302.67  1327.4 2306.91  1367.7 2311.77
#Mann= 3 , 0 , 0
       0      .1       0   680.4    .045       0   695.4      .1       0
#XS Ineff= 2 , 0
                         1144.35         2276.47
Permanent Ineff=
       F       F
Bank Sta=680.4,695.4
XS Rating Curve= 0 ,0
Exp/Cntr=0.3,0.1

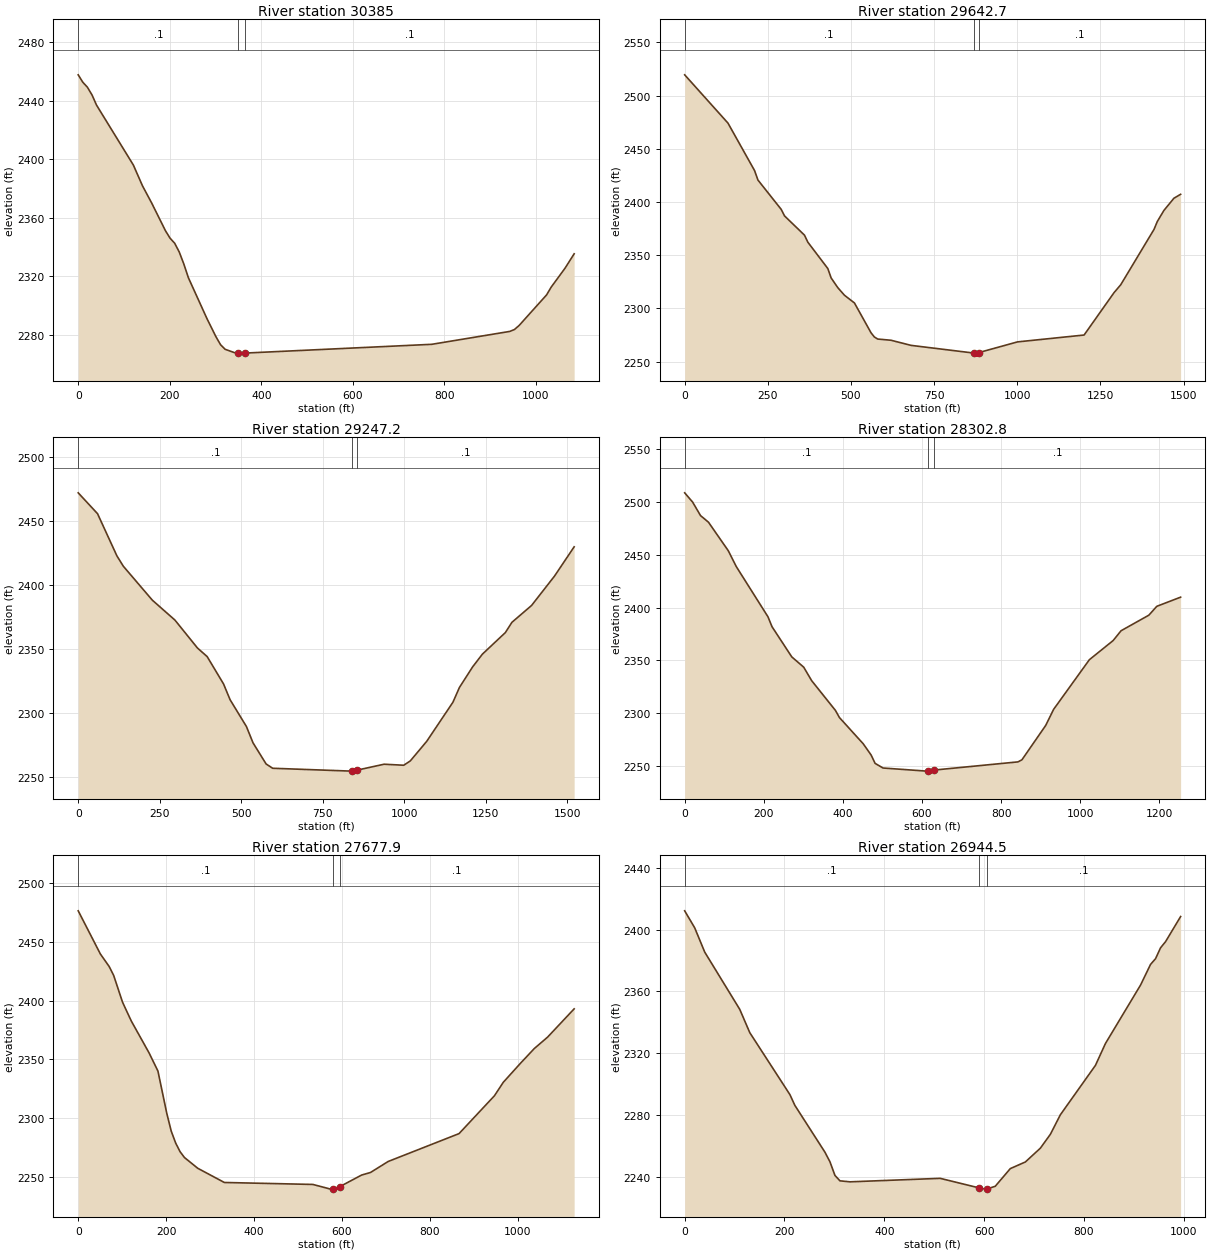
Type RM Length L Ch R = 1 ,30385   ,743.4,742.3,741.3
XS GIS Cut Line= 2
     2227581.543      376282.146      2226718.35      376936.816
#Sta/Elev= 30
       0 2457.67      10 2452.63    20.1  2449.2    30.1 2443.96    40.1 2436.94
   120.4  2396.1   140.4 2381.86   160.5 2370.11   190.6 2351.17   200.6  2346.1
   210.7 2342.65   220.7 2336.66   230.7 2328.48   240.8    2319   280.9 2291.38
   300.9 2278.77     311  2273.3     321 2270.18   341.1 2267.93     350 2267.64
   361.1 2267.57     365 2267.61   772.4 2273.59   942.9 2282.41     953  2283.7
     963  2286.4  1023.2 2307.35  1033.2 2312.64  1063.3  2325.5  1083.4 2335.41
#Mann= 3 , 0 , 0
       0      .1       0     350    .045       0     365      .1       0
Bank Sta=350,365
XS Rating Curve= 0 ,0
Exp/Cntr=0.3,0.1

Type RM Length L Ch R = 1 ,29642.7 ,385.3,395.5,405.7
XS GIS Cut Line= 3
     2227499.103      375966.935     2226868.681      375962.086
     2226209.162      376514.918
#Sta/Elev= 30
       0 2519.49   130.1 2474.16   210.2 2429.48   220.2 2420.67   290.2 2393.09
   300.2 2386.95   360.2 2368.87   370.3 2362.26   430.3 2337.54   440.3 2328.69
   460.3 2319.56   480.3 2312.45   510.4 2305.16   560.4 2277.09   570.4 2273.18
   580.4 2271.26   620.4 2270.13   680.5 2265.33     869 2258.11   870.6 2258.04
     884 2258.53  1000.7  2268.6  1200.8 2275.04  1290.9 2314.88  1310.9 2322.23
    1411 2374.25    1421 2381.73    1441 2392.18    1471 2403.57    1491 2407.24
#Mann= 3 , 0 , 0
       0      .1       0     869    .045       0     884      .1       0
Bank Sta=869,884
XS Rating Curve= 0 ,0
Exp/Cntr=0.3,0.1

Type RM Length L Ch R = 1 ,29247.2 ,949.8,944.4,939
XS GIS Cut Line= 3
     2227062.657      375317.115     2226907.476      375680.821
     2225816.361      375957.236
#Sta/Elev= 30
       0 2472.32    59.3 2456.01   118.6 2423.08   138.4 2414.95   227.4 2388.41
   296.6 2372.88   365.8 2351.02   395.4 2344.36   445.7 2322.97   465.8 2310.63
     516 2289.63   536.1 2276.94   576.3 2260.41   596.4 2257.06   837.6 2254.82
   841.1 2254.88   856.1 2255.64   938.1 2260.22   998.4 2259.42  1018.5 2262.81
  1068.8 2278.09  1149.2 2308.65  1169.3 2320.25  1209.5 2336.24  1239.6 2346.24
    1310 2363.09  1330.1  2371.1  1390.4 2384.29  1460.7 2407.22    1521 2430.12
#Mann= 3 , 0 , 0
       0      .1       0   841.1    .045       0   856.1      .1       0
Bank Sta=841.1,856.1
XS Rating Curve= 0 ,0
Exp/Cntr=0.3,0.1

Type RM Length L Ch R = 1 ,28302.8 ,626.8,625.3,623.9
XS GIS Cut Line= 2
     2226820.187      374667.296     2225709.674      375249.224
#Sta/Elev= 30
       0 2508.68    20.1 2499.89    40.1  2487.1    60.2 2480.83   110.3  2453.8
   130.4 2438.85   210.6 2391.23   220.7 2381.93   270.8 2353.24   300.9 2343.53
     321 2330.75   381.1 2302.58   391.2 2295.82   451.4 2270.93   471.4 2260.28
   481.4 2252.39   501.5 2247.99   611.8 2245.04   615.8 2245.18   630.8 2246.06
   842.5 2253.79   852.6 2255.75   912.7 2288.32   932.8 2303.59  1023.1 2350.58
  1083.2 2368.73  1103.3 2378.04  1173.5 2392.78  1193.6 2401.17  1253.8 2409.83
#Mann= 3 , 0 , 0
       0      .1       0   615.8    .045       0   630.8      .1       0
Bank Sta=615.8,630.8
XS Rating Curve= 0 ,0
Exp/Cntr=0.3,0.1

Type RM Length L Ch R = 1 ,27677.9 ,732.3,732.9,733.6
XS GIS Cut Line= 2
     2226301.301      374211.452     2225365.367      374841.874
#Sta/Elev= 30
       0 2476.51    50.4 2439.75    70.5 2429.03    80.6 2421.52   100.8 2398.74
   110.8 2390.61   120.9 2382.53   161.2 2355.46   181.4 2339.96   201.5 2303.95
   211.6 2288.82   221.7 2278.65   231.7 2271.28   241.8 2266.26     272 2257.11
   332.5 2245.01     534 2243.33   574.3 2239.34   579.9 2239.64   594.9 2241.42
   644.8 2251.32     665 2253.52   705.3 2262.91   866.5 2286.65   947.1 2318.94
   967.2  2330.4  1007.6 2347.13  1037.8 2359.17    1068 2368.89  1128.4 2392.97
#Mann= 3 , 0 , 0
       0      .1       0   579.9    .045       0   594.9      .1       0
Bank Sta=579.9,594.9
XS Rating Curve= 0 ,0
Exp/Cntr=0.3,0.1

Type RM Length L Ch R = 1 ,26944.5 ,559.4,558.1,556.8
XS GIS Cut Line= 2
     2225918.198      373697.415     2225045.306      374172.657
#Sta/Elev= 30
       0 2412.16    20.1 2401.16    40.2 2385.44   110.4 2348.38   130.5  2333.3
   210.8 2293.27   220.9 2286.21   281.1 2255.95   291.1 2249.77   301.2  2240.9
   311.2 2237.41   331.3 2236.76     512 2239.02     590 2232.84   602.4 2232.04
     605 2232.06   622.4 2233.89   652.6 2245.33   682.7  2249.6   712.8 2258.54
   732.9 2267.53   752.9 2280.16   823.2 2312.13   843.3 2326.32   913.6  2364.1
   933.6 2377.46   943.7 2381.21   953.7 2388.22   963.8 2392.25   993.9 2408.46
#Mann= 3 , 0 , 0
       0      .1       0     590    .045       0     605      .1       0
Bank Sta=590,605
XS Rating Curve= 0 ,0
Exp/Cntr=0.3,0.1