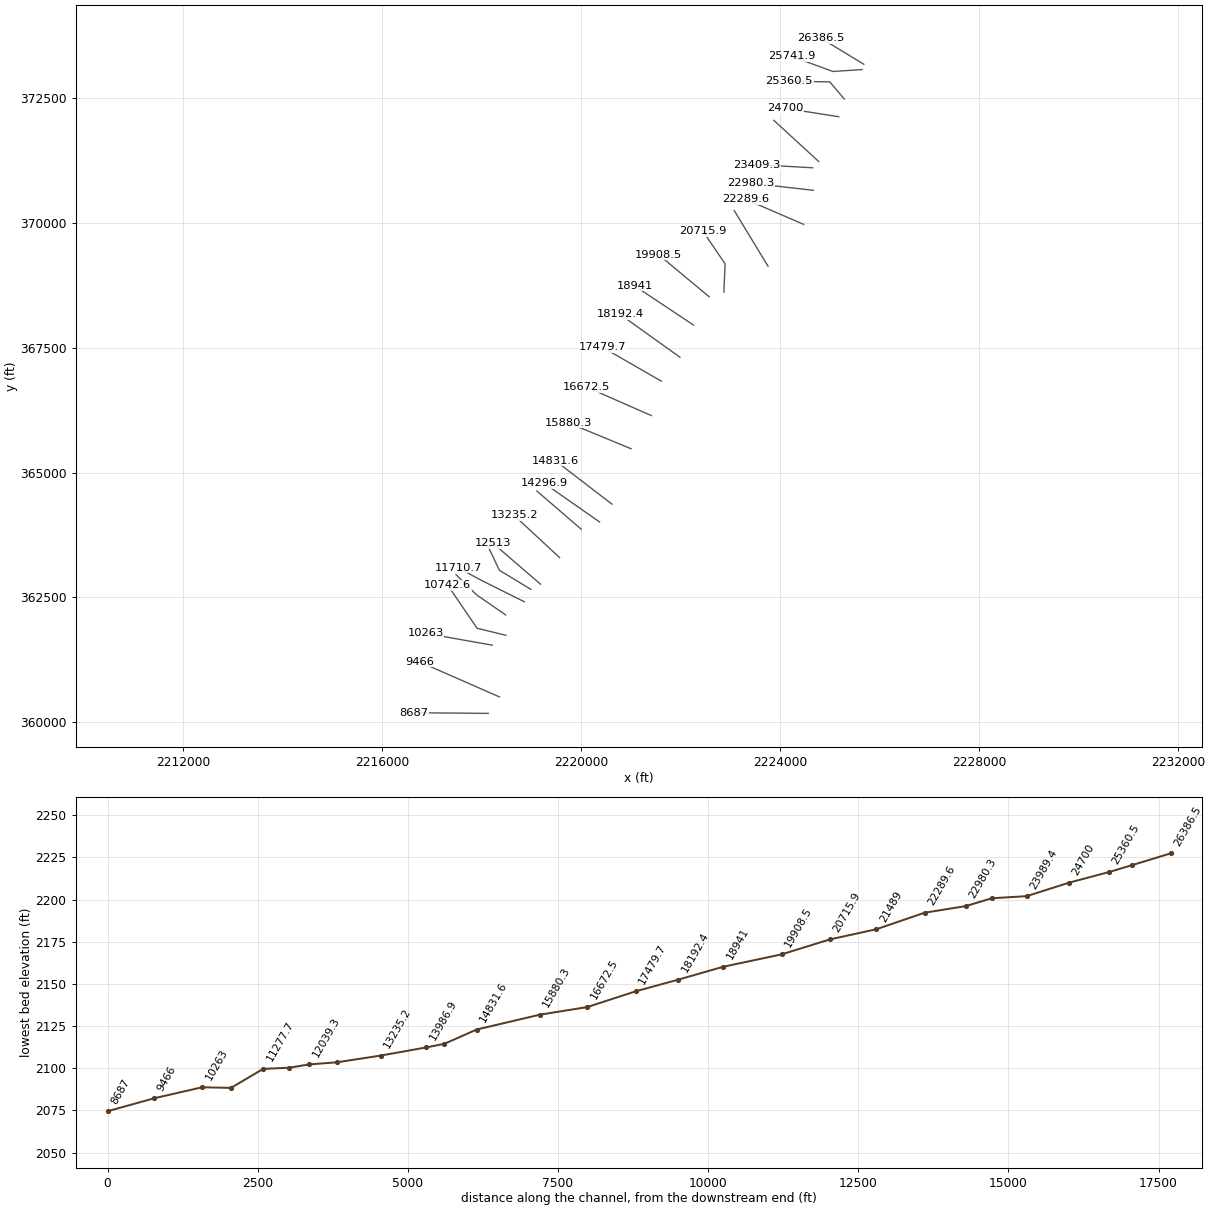
HEC-RAS study NFrkAntCk.prj: NFrkAntCk

--- NFrkAntCk.g01 (geometry) --- (continued)

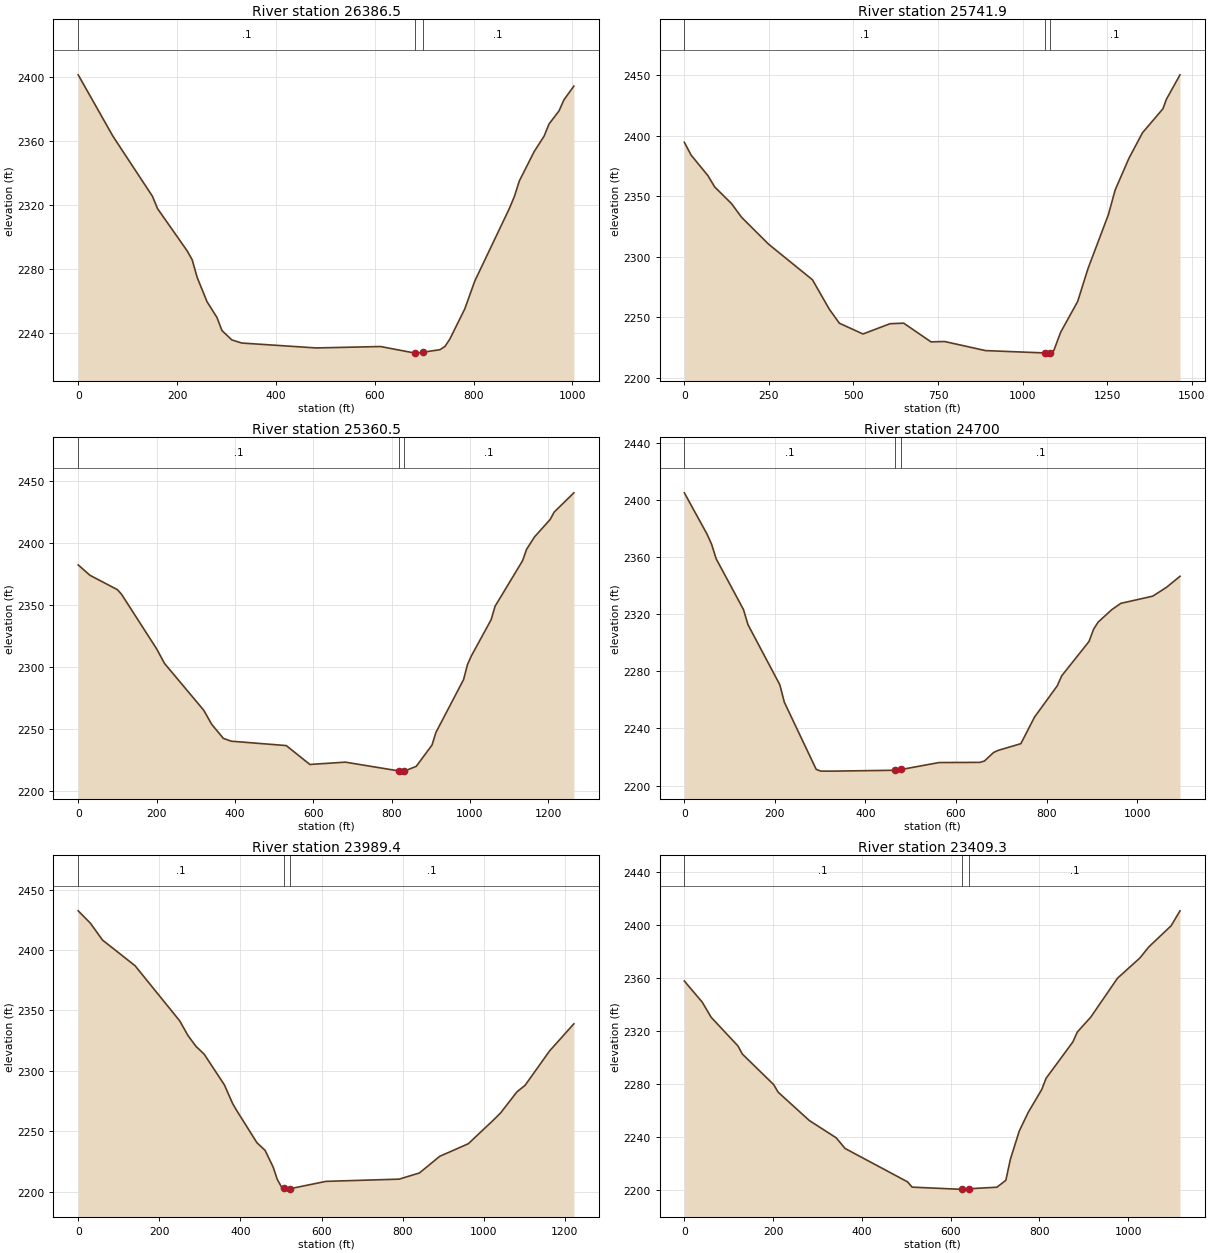
Type RM Length L Ch R = 1 ,26386.5 ,640,644.4,648.8
XS GIS Cut Line= 2
     2225680.578      373183.379     2224822.234      373702.265
#Sta/Elev= 30
       0  2401.2    70.2  2362.9   150.4 2325.29   160.5 2317.67   220.7 2291.16
   230.7 2285.65   240.7 2274.72   260.8 2259.45   280.8 2249.67   290.9 2241.48
   310.9 2235.64     331 2233.68   481.4 2230.62   611.8  2231.5     682 2227.38
     697 2227.93   732.2 2229.53   742.2 2231.57   752.2 2236.24   782.3 2254.99
   802.4 2272.31   872.6  2317.8   882.6 2325.15   892.7 2334.92   922.8 2353.31
   942.8  2362.9   952.8  2370.5   972.9 2378.62   982.9 2385.54    1003 2394.16
#Mann= 3 , 0 , 0
       0      .1       0     682    .045       0     697      .1       0
Bank Sta=682,697
XS Rating Curve= 0 ,0
Exp/Cntr=0.3,0.1

Type RM Length L Ch R = 1 ,25741.9 ,373.5,381.2,388.8
XS GIS Cut Line= 3
     2225646.632      373076.692     2225059.854      373037.897
     2224235.456      373338.559
#Sta/Elev= 30
       0 2394.77    19.9  2384.2    69.8 2367.16    89.7 2357.84   139.5 2344.04
   169.4 2332.67   249.2 2310.47   378.8 2281.05   428.6 2256.75   458.5 2245.11
   528.3 2236.23   608.2 2244.72   648.6 2245.18   729.3 2229.71   769.6 2229.99
   890.6 2222.48  1066.4 2220.54  1072.2 2220.39  1081.4 2220.47  1092.4 2222.49
  1112.6 2237.59    1163 2263.12  1193.2 2290.01  1253.8 2334.87  1273.9 2355.31
  1314.3 2381.35  1354.6  2402.6  1415.1 2422.46  1425.2 2430.22  1465.6 2450.55
#Mann= 3 , 0 , 0
       0      .1       0  1066.4    .045       0  1081.4      .1       0
Bank Sta=1066.4,1081.4
XS Rating Curve= 0 ,0
Exp/Cntr=0.3,0.1

Type RM Length L Ch R = 1 ,25360.5 ,663.7,660.7,657.7
XS GIS Cut Line= 3
     2225287.776      372485.065     2224996.812      372829.372
     2224182.112       372843.92
#Sta/Elev= 30
       0 2382.22      30 2373.87   100.2 2362.28   110.2 2358.78   200.4 2314.64
   220.4 2302.95   320.6 2265.29   340.6 2254.12   370.6 2242.68   390.7  2240.4
   531.3 2236.88   591.6 2221.67   682.2 2223.54     818 2216.53     823 2216.32
     833 2216.34   863.2 2220.18   903.5 2237.34   913.5 2247.49     984 2289.95
     994 2302.03  1004.1 2309.12  1054.4 2338.15  1064.4 2348.91  1134.8 2385.66
  1144.9 2394.74    1165 2404.68  1205.3 2418.82  1215.3 2424.68  1265.6 2440.19
#Mann= 3 , 0 , 0
       0      .1       0     818    .045       0     833      .1       0
Bank Sta=818,833
XS Rating Curve= 0 ,0
Exp/Cntr=0.3,0.1

Type RM Length L Ch R = 1 ,24700   ,724,710.5,697.1
XS GIS Cut Line= 2
      2225176.24      372131.058     2224094.823      372300.787
#Sta/Elev= 30
       0 2404.82    50.2 2375.88    60.3 2368.73    70.3 2358.66   130.6 2323.14
   140.6 2312.54   210.9  2270.5   220.9 2258.25   291.2 2211.31   301.3 2210.08
   331.4 2210.07   464.2 2210.68   479.2 2211.22   562.4 2216.07   652.8  2216.2
   662.8 2217.15   682.9  2223.1     693 2224.58   743.2 2229.28   773.3 2247.83
   823.5 2269.71   833.5 2276.78   893.8 2300.82   903.8 2309.34   913.9 2314.36
     944 2323.05   964.1 2327.48  1034.4  2332.5  1064.5 2338.59  1094.7 2346.41
#Mann= 3 , 0 , 0
       0      .1       0   464.2    .045       0   479.2      .1       0
Bank Sta=464.2,479.2
XS Rating Curve= 0 ,0
Exp/Cntr=0.3,0.1

Type RM Length L Ch R = 1 ,23989.4 ,563.8,580.2,596.6
XS GIS Cut Line= 2
      2224773.74      371233.919     2223871.751      372058.317
#Sta/Elev= 30
       0 2432.37      30 2422.16    60.1 2408.13   140.2 2386.94   250.4 2341.25
   270.4  2329.3   290.5 2320.15   310.5 2313.76   360.6 2288.24   380.6 2272.96
   390.6 2267.22   440.7 2240.43   460.7 2234.17   480.8 2220.19   490.8 2210.16
   500.8    2204     507 2202.78   510.8 2202.04     522 2202.37     611 2208.46
   791.3 2210.31   841.4 2215.44   891.4 2229.21   961.6 2239.57  1021.6 2258.52
  1041.7  2265.2  1081.8 2282.58  1101.8 2287.95  1161.9 2316.31    1222 2338.86
#Mann= 3 , 0 , 0
       0      .1       0     507    .045       0     522      .1       0
Bank Sta=507,522
XS Rating Curve= 0 ,0
Exp/Cntr=0.3,0.1

Type RM Length L Ch R = 1 ,23409.3 ,431.6,428.9,426.1
XS GIS Cut Line= 2
     2224652.504      371107.835     2223537.142      371170.877
#Sta/Elev= 30
       0 2357.57    40.3 2341.66    60.4 2330.26   120.8 2308.67   130.8 2302.54
   201.3 2279.55   211.4 2273.83   281.8 2252.44   342.2 2239.46   362.3 2231.42
   503.2 2206.25   513.3 2202.29   613.9 2200.79   625.7 2200.85   640.7 2201.07
   704.5 2202.24   724.6 2207.44   734.7 2223.12   754.8 2244.54     775  2258.6
   805.2 2275.66   815.2 2284.24   875.6 2311.66   885.7 2319.13   915.9 2330.33
   976.2 2359.67  1026.6  2374.9  1046.7 2383.23    1097 2399.16  1117.1 2410.45
#Mann= 3 , 0 , 0
       0      .1       0   625.7    .045       0   640.7      .1       0
Bank Sta=625.7,640.7
XS Rating Curve= 0 ,0
Exp/Cntr=0.3,0.1

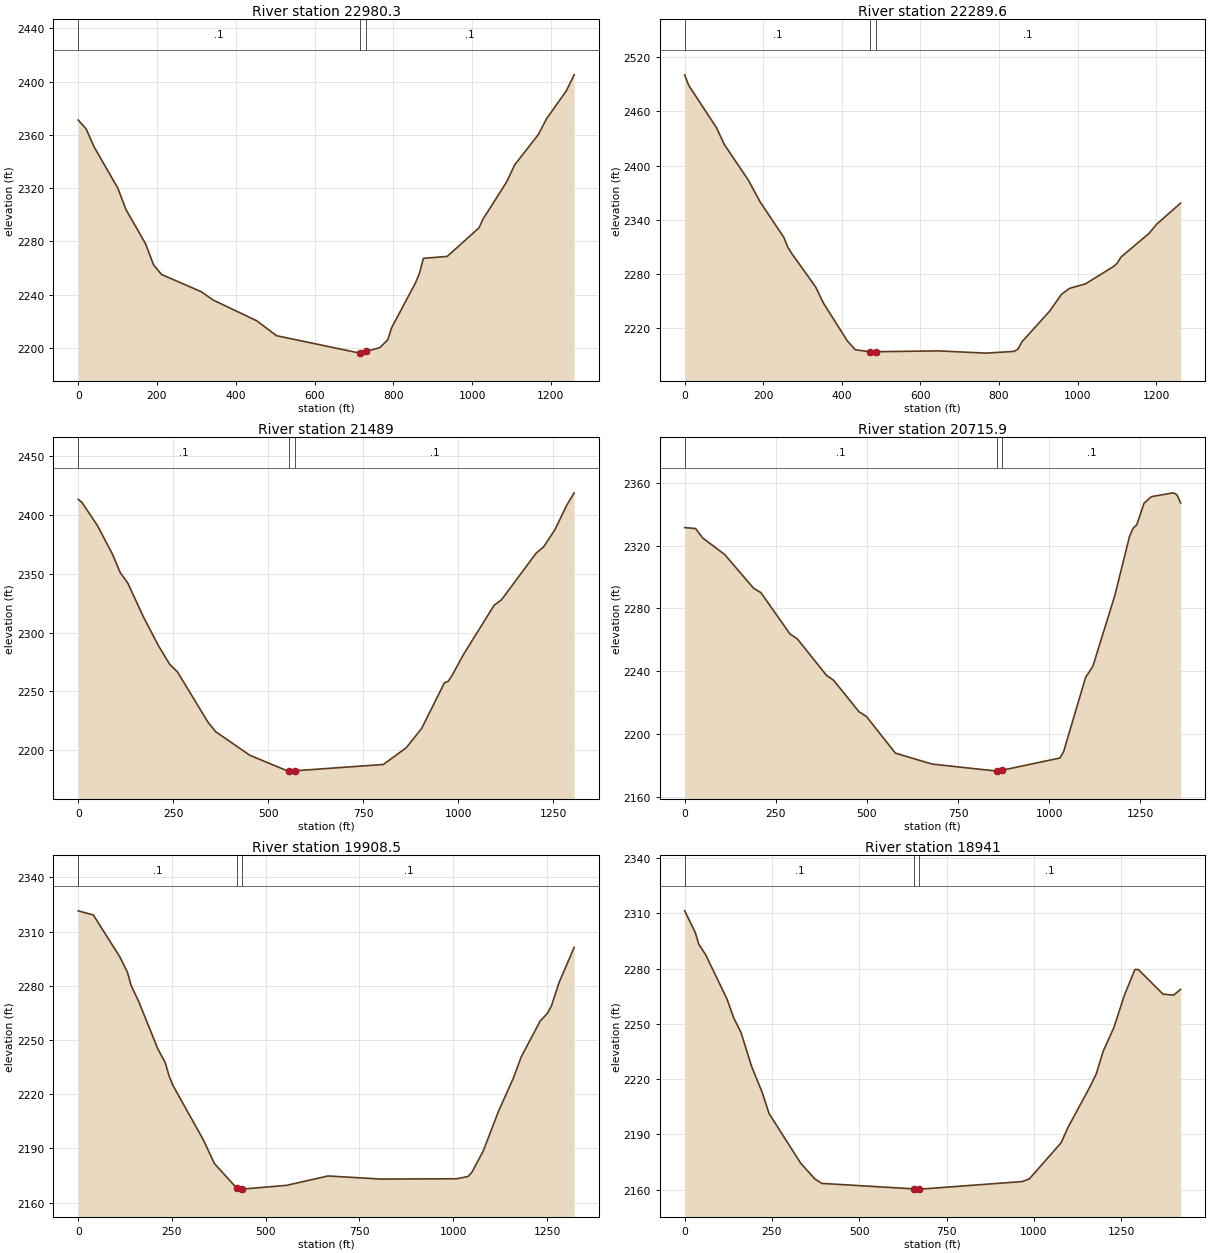
Type RM Length L Ch R = 1 ,22980.3 ,699,690.6,680.1
XS GIS Cut Line= 2
     2224667.053       370656.84     2223415.907      370797.473
#Sta/Elev= 30
       0 2371.14    20.1 2364.56    40.3 2350.99   100.7 2319.96   120.9 2304.14
   171.2 2278.14   191.4 2262.38   211.5 2255.22   312.2 2242.31   342.4 2236.06
   453.2 2220.46   503.6 2209.25   715.1 2196.18     716 2196.24     731 2197.45
   765.5  2200.3   785.6 2206.07   795.7 2215.28   856.1 2248.82   866.2 2256.04
   876.3 2267.35   936.7 2268.78  1017.3 2290.18  1027.4 2296.66  1087.8 2324.78
  1107.9 2337.43  1168.4  2360.4  1188.5 2371.94  1238.9 2392.97    1259 2405.09
#Mann= 3 , 0 , 0
       0      .1       0     716    .045       0     731      .1       0
Bank Sta=716,731
XS Rating Curve= 0 ,0
Exp/Cntr=0.3,0.1

Type RM Length L Ch R = 1 ,22289.6 ,814.5,800.6,786.7
XS GIS Cut Line= 2
     2224473.077      369973.074      2223314.07      370472.563
#Sta/Elev= 30
       0 2500.61    10.1 2489.08    80.8 2442.13     101 2423.34   161.5 2384.31
   191.8 2359.94   252.4 2320.41   262.5 2309.59   272.6 2302.58   333.2 2265.57
   353.4 2247.44     414 2205.74   434.2 2195.96   471.2 2193.67   486.2 2193.79
   646.2 2194.69   767.3 2192.21     838 2194.11   848.1 2196.55   858.2 2204.71
   928.9 2238.77   959.2 2257.54   979.4 2263.97  1019.7 2268.92  1090.4 2287.91
  1100.5 2291.69  1110.6 2298.74  1181.3 2324.74  1201.5 2335.18  1262.1 2358.49
#Mann= 3 , 0 , 0
       0      .1       0   471.2    .045       0   486.2      .1       0
Bank Sta=471.2,486.2
XS Rating Curve= 0 ,0
Exp/Cntr=0.3,0.1

Type RM Length L Ch R = 1 ,21489   ,772.2,773.1,773.9
XS GIS Cut Line= 2
     2223755.365      369134.128     2223076.449       370249.49
#Sta/Elev= 30
       0 2413.03      10 2410.36    50.2 2391.04    90.4 2366.41   110.5 2350.91
   130.6 2341.97   170.8 2313.86   210.9 2289.07   241.1 2272.96   261.2 2266.68
   341.5 2224.06   361.6 2215.99     452 2195.84   552.4 2182.44   555.4 2182.47
   570.4 2182.73   803.5 2188.08   863.8 2202.36     904  2218.6   964.2 2257.37
   974.3 2258.72   984.3 2263.64  1014.5 2281.46  1094.8 2323.09  1114.9 2327.99
  1205.3 2367.26  1225.4 2372.77  1255.5 2387.49  1285.6 2407.69  1305.7 2418.56
#Mann= 3 , 0 , 0
       0      .1       0   555.4    .045       0   570.4      .1       0
Bank Sta=555.4,570.4
XS Rating Curve= 0 ,0
Exp/Cntr=0.3,0.1

Type RM Length L Ch R = 1 ,20715.9 ,800.7,807.4,815.3
XS GIS Cut Line= 3
     2222867.925      368615.242     2222892.172      369182.622
     2222446.027      369837.291
#Sta/Elev= 30
       0 2331.42    29.9 2330.79    49.8 2324.74   109.6 2314.32   189.3 2292.74
   209.2 2289.98   288.9 2263.66   308.9 2260.59   388.6 2237.48   408.5 2234.23
   478.2 2214.19   498.2 2211.25   577.9 2187.88   678.2 2180.91   856.3 2176.44
   858.7 2176.42   871.3 2177.02  1029.2 2184.77  1039.2 2188.81  1099.4 2235.98
  1119.4 2243.15  1179.6 2288.14  1219.7 2325.57  1229.8 2330.97  1239.8 2333.18
  1259.8  2346.9  1279.9 2351.09  1340.1 2353.53  1350.1 2352.28  1360.1 2347.09
#Mann= 3 , 0 , 0
       0      .1       0   856.3    .045       0   871.3      .1       0
Bank Sta=856.3,871.3
XS Rating Curve= 0 ,0
Exp/Cntr=0.3,0.1

Type RM Length L Ch R = 1 ,19908.5 ,965.6,967.5,968.2
XS GIS Cut Line= 2
     2222572.111      368523.103     2221553.737      369366.899
#Sta/Elev= 30
       0  2321.5    40.4 2319.19     111 2296.02   131.2 2287.57   141.3 2280.08
   161.5 2271.26     212 2245.26   232.2 2237.46   242.3 2230.15   252.4 2224.96
   333.2 2194.97   363.4 2181.62     423 2168.01   434.1 2167.51     438 2167.54
   555.3  2169.6   666.3 2174.79   807.6 2173.07  1009.6 2173.25  1039.8 2174.52
    1050  2176.9  1080.2 2188.68  1120.6 2210.51    1161 2229.22  1181.2 2240.61
  1231.7 2260.46  1251.9 2264.98    1262 2268.95  1282.1 2281.73  1322.5 2301.26
#Mann= 3 , 0 , 0
       0      .1       0     423    .045       0     438      .1       0
Bank Sta=423,438
XS Rating Curve= 0 ,0
Exp/Cntr=0.3,0.1

Type RM Length L Ch R = 1 ,18941   ,752.2,748.5,744.7
XS GIS Cut Line= 2
       2222256.9      367955.723     2221073.646      368741.326
#Sta/Elev= 30
       0 2311.41    30.2  2299.7    40.3 2293.34    60.4 2287.43   120.9  2263.6
     141 2252.98   161.2 2245.39   191.4    2227   221.6 2212.97   241.8 2201.25
   332.4 2174.26   372.7 2165.78   392.8 2163.33   657.2 2160.35   672.2 2160.23
   674.9 2160.22     967 2164.33   987.2 2165.81  1077.8 2185.34    1098 2193.82
  1158.4    2215  1178.6 2222.77  1198.7 2235.22  1228.9 2247.84  1259.1 2265.42
  1289.4 2279.55  1299.4 2279.49  1369.9 2266.13  1400.2 2265.63  1420.3 2268.73
#Mann= 3 , 0 , 0
       0      .1       0   657.2    .045       0   672.2      .1       0
Bank Sta=657.2,672.2
XS Rating Curve= 0 ,0
Exp/Cntr=0.3,0.1

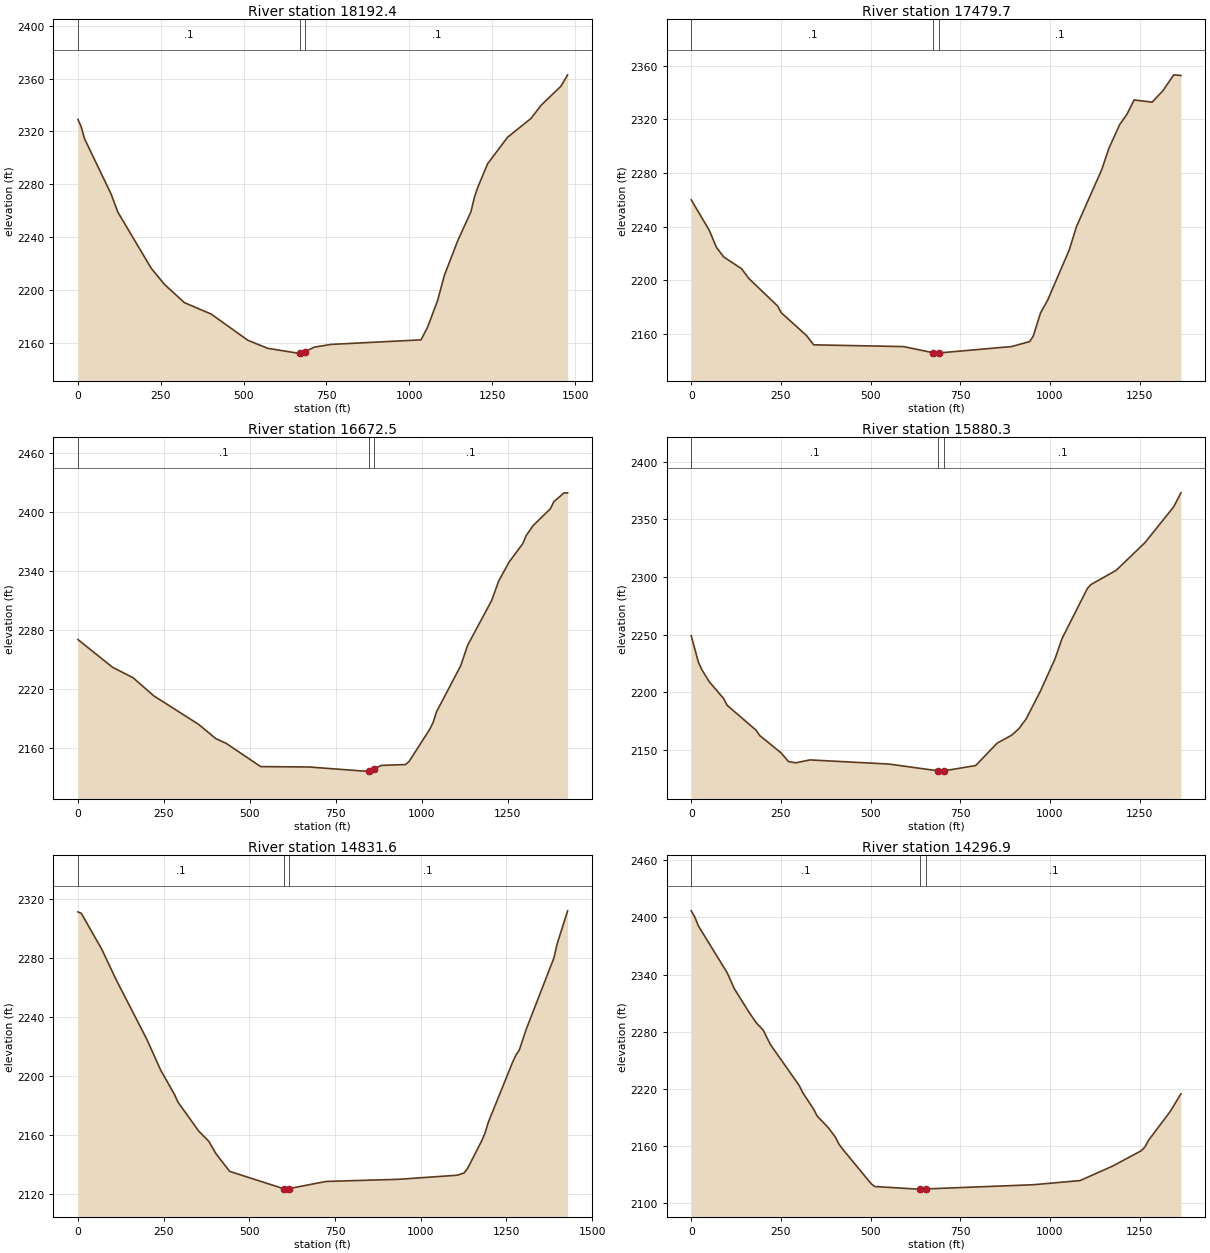
Type RM Length L Ch R = 1 ,18192.4 ,708.8,712.7,716.6
XS GIS Cut Line= 2
     2221985.333      367310.753     2220782.682      368169.097
#Sta/Elev= 30
       0 2329.12      10 2323.52    20.1  2314.5   100.5 2272.56   120.6 2259.06
   221.1 2216.73   261.3 2204.46   321.6 2190.68     402 2182.11   512.6 2162.31
   572.9  2156.2   663.4 2152.58   670.3 2152.78   685.3 2153.72   713.6 2157.14
   763.9 2159.17  1035.3 2162.61  1055.4 2172.38  1085.5 2192.54  1105.6 2211.26
  1145.8 2237.39    1186 2259.49  1196.1 2270.15  1206.2 2277.64  1236.3 2295.69
  1296.6 2315.72    1367 2329.84  1397.1 2339.73  1457.4 2354.21  1477.5  2362.8
#Mann= 3 , 0 , 0
       0      .1       0   670.3    .045       0   685.3      .1       0
Bank Sta=670.3,685.3
XS Rating Curve= 0 ,0
Exp/Cntr=0.3,0.1

Type RM Length L Ch R = 1 ,17479.7 ,804.1,807.2,810.3
XS GIS Cut Line= 2
     2221611.245      366831.316     2220427.067      367510.245
#Sta/Elev= 30
       0 2259.97    50.2 2237.31    70.3 2224.53    90.3 2217.43   140.5 2208.55
   160.6 2201.31   240.9 2180.74   250.9 2175.78   321.2  2158.8   341.2 2151.82
   592.2  2150.5     675 2145.89   682.5 2145.63     690 2145.76   893.3 2150.54
   943.5 2154.26   953.5  2158.4   973.6 2175.56   993.6 2185.19  1053.9 2222.73
  1073.9    2240  1144.2 2282.46  1164.3 2298.43  1194.4 2316.15  1214.4  2323.7
  1234.5 2334.45  1284.7 2332.83  1314.8 2341.35  1344.9  2353.2    1365 2352.72
#Mann= 3 , 0 , 0
       0      .1       0     675    .045       0     690      .1       0
Bank Sta=675,690
XS Rating Curve= 0 ,0
Exp/Cntr=0.3,0.1

Type RM Length L Ch R = 1 ,16672.5 ,791.7,792.3,792.8
XS GIS Cut Line= 2
     2221408.255      366142.047     2220103.765      366714.276
#Sta/Elev= 30
       0 2270.28   100.3 2242.12   160.5 2231.35   220.7 2212.93   351.1  2183.9
   401.3 2169.33   431.4 2164.57   531.7  2140.9   672.1  2140.5   832.6 2136.29
   846.1 2136.73   861.1  2138.6   882.8  2142.1     953 2143.02     963 2145.96
  1023.2 2178.72  1033.2 2185.76  1043.3 2196.79  1113.5 2243.54  1133.6 2264.34
  1203.8 2310.12  1223.8 2329.66  1253.9 2348.92  1294.1 2367.89  1304.1 2376.12
  1324.2 2386.22  1374.3 2403.35  1384.4 2410.54  1414.4 2419.58  1424.5  2419.5
#Mann= 3 , 0 , 0
       0      .1       0   846.1    .045       0   861.1      .1       0
Bank Sta=846.1,861.1
XS Rating Curve= 0 ,0
Exp/Cntr=0.3,0.1

Type RM Length L Ch R = 1 ,15880.3 ,1054.6,1048.7,1042.7
XS GIS Cut Line= 2
     2221002.473       365476.82     2219740.448      365996.934
#Sta/Elev= 30
       0 2249.14    20.1 2226.11    30.1 2219.41    50.2 2209.26    90.3 2194.68
   100.4 2188.74   180.7 2167.28   190.7 2162.69   250.9 2147.47     271 2140.05
   291.1 2138.94   331.2 2141.47     552 2137.86   688.4 2131.98   692.5 2131.75
   703.4 2131.95   792.9  2136.6   853.1  2156.1   893.3 2162.92   913.4 2168.58
   933.4 2176.93   973.6 2201.31  1013.7 2228.78  1033.8 2246.81    1104 2289.97
  1114.1 2293.46  1184.3 2305.78  1264.6 2329.77  1344.9 2360.87    1365 2372.99
#Mann= 3 , 0 , 0
       0      .1       0   688.4    .045       0   703.4      .1       0
#XS Ineff= 2 , 0
          330.65  2141.3
Permanent Ineff=
       F       F
Bank Sta=688.4,703.4
XS Rating Curve= 0 ,0
Exp/Cntr=0.3,0.1

Type RM Length L Ch R = 1 ,14831.6 ,535.3,534.8,534.2
XS GIS Cut Line= 2
     2220617.802      364367.166     2219483.042      365235.209
#Sta/Elev= 30
       0 2311.16    10.1 2310.11    70.4 2285.46   110.7 2265.53   201.2 2224.61
   241.5 2203.78   281.7 2187.26   291.8 2182.12   352.1 2162.49   382.3 2155.32
   402.4 2147.13   442.7 2135.03   600.5 2123.24   603.7 2122.97   615.5 2123.33
   724.4 2128.19   935.7 2129.63  1106.7 2132.42  1126.9 2133.96  1136.9 2137.03
  1177.2 2155.36  1187.2 2160.63  1197.3 2168.32  1267.7 2208.83  1277.8 2213.94
  1287.8 2217.42    1308 2231.53  1388.4 2279.67  1398.5 2289.66  1428.7 2311.87
#Mann= 3 , 0 , 0
       0      .1       0   600.5    .045       0   615.5      .1       0
Bank Sta=600.5,615.5
XS Rating Curve= 0 ,0
Exp/Cntr=0.3,0.1

Type RM Length L Ch R = 1 ,14296.9 ,311.6,309.9,308.1
XS GIS Cut Line= 2
     2220369.311      364009.795     2219248.957      364789.558
#Sta/Elev= 30
       0    2407      10 2400.52    20.1  2391.1   100.4  2341.8   120.4 2324.99
   160.6 2300.78   180.7 2289.59   200.7 2281.64   220.8 2266.42   301.1 2223.43
   311.1 2215.77   341.2  2198.6   351.3 2191.25   381.4  2179.4   401.5  2169.4
   411.5 2162.05   421.5 2156.88   501.8 2120.15   511.9 2117.26   632.3 2114.54
   638.7 2114.55   653.7 2114.74   953.5 2119.16    1084 2123.53  1174.3 2138.69
  1254.6 2154.94  1264.6 2158.78  1274.7 2165.83  1334.9 2195.99    1365 2214.67
#Mann= 3 , 0 , 0
       0      .1       0   638.7    .045       0   653.7      .1       0
Bank Sta=638.7,653.7
XS Rating Curve= 0 ,0
Exp/Cntr=0.3,0.1

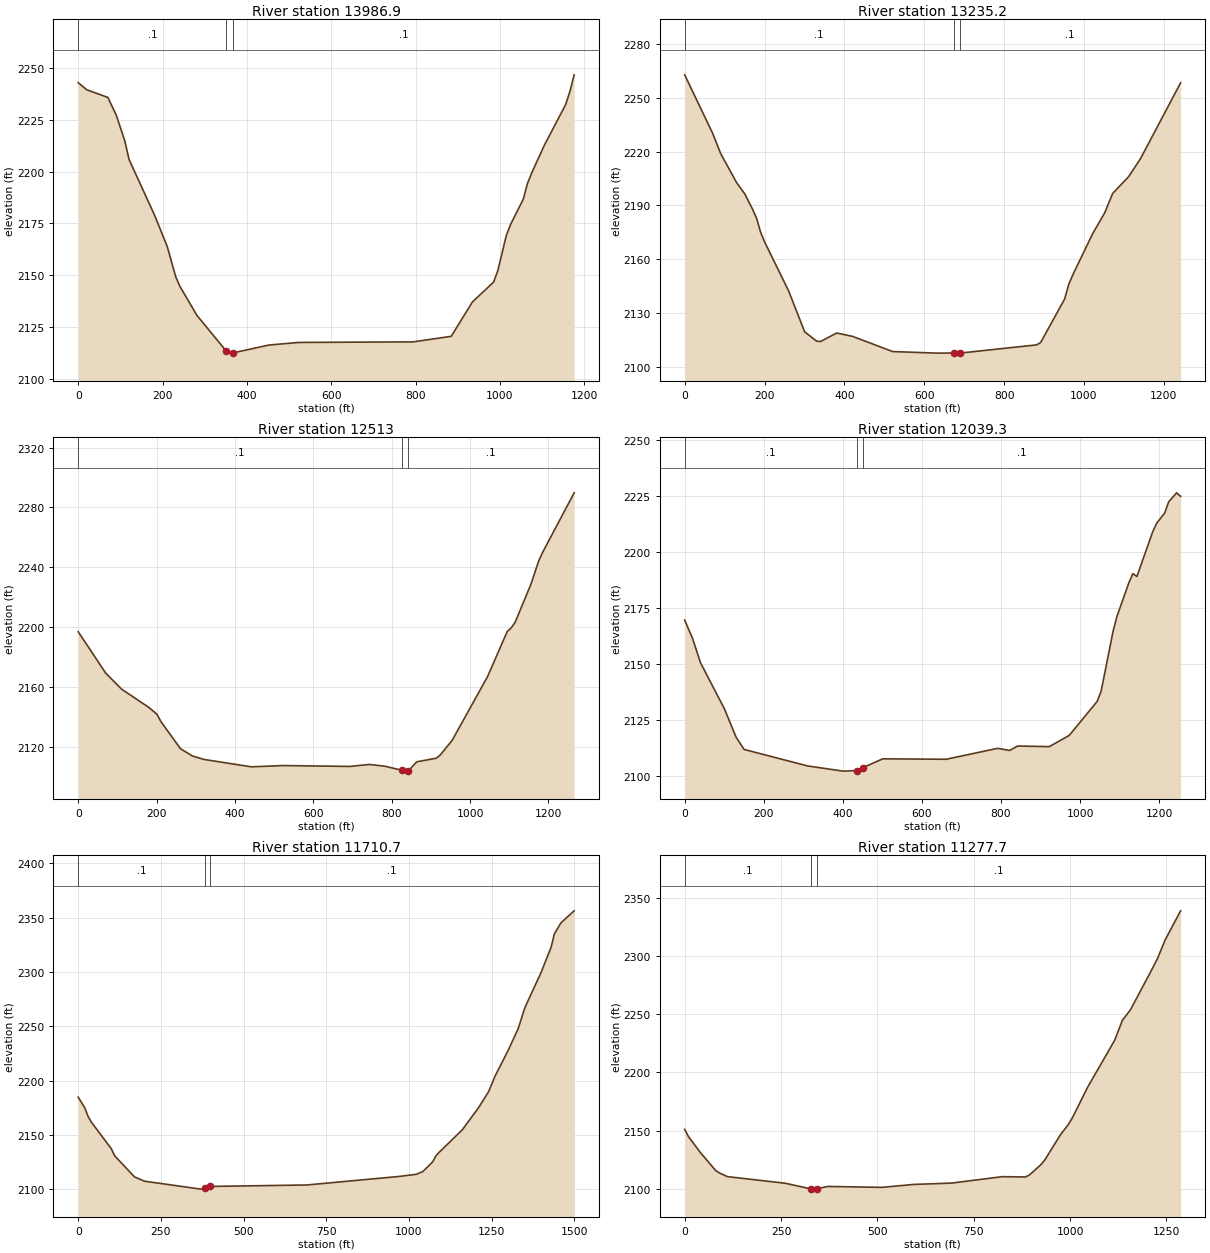
Type RM Length L Ch R = 1 ,13986.9 ,749.8,751.6,753.4
XS GIS Cut Line= 2
     2220001.928      363862.828     2219109.638      364629.034
#Sta/Elev= 30
       0 2242.93    20.1 2239.54    70.4 2235.82    90.5 2227.13   110.6 2214.75
   120.6 2205.83   180.9 2179.05   211.1 2163.86   231.2 2149.26   241.2 2144.59
   281.5 2130.56   351.4 2113.26   361.9 2112.34   366.4 2112.42   452.4 2116.25
   522.7  2117.5   794.1 2117.77   884.6 2120.46   934.9 2137.07   985.1 2146.64
   995.2 2152.25  1015.3 2169.22  1025.3 2174.45  1055.5  2186.7  1065.5 2194.31
  1075.6 2199.42  1105.8 2212.87    1156 2232.38  1166.1 2238.72  1176.1 2246.73
#Mann= 3 , 0 , 0
       0      .1       0   351.4    .045       0   366.4      .1       0
Bank Sta=351.4,366.4
XS Rating Curve= 0 ,0
Exp/Cntr=0.3,0.1

Type RM Length L Ch R = 1 ,13235.2 ,724,722.3,720.6
XS GIS Cut Line= 2
     2219565.482      363295.448     2218653.794      364139.244
#Sta/Elev= 30
       0 2262.85    70.1 2230.19    90.2 2218.88   130.2 2202.68   150.3  2196.5
   170.3 2187.75   180.3  2182.7   190.3 2174.92   200.4 2169.55   260.5 2142.21
   300.5 2119.48   330.6 2114.22   340.6 2114.07   380.7 2118.78   420.8 2116.89
   520.9 2108.44   631.1 2107.56   674.1 2107.63   689.1 2107.57   881.6 2112.17
   891.6 2113.47   951.7 2137.76   961.7 2145.74   971.8 2151.09  1021.8 2174.15
  1051.9 2185.77  1071.9 2196.62    1112 2206.02  1142.1 2216.23  1242.2 2258.41
#Mann= 3 , 0 , 0
       0      .1       0   674.1    .045       0   689.1      .1       0
Bank Sta=674.1,689.1
XS Rating Curve= 0 ,0
Exp/Cntr=0.3,0.1

Type RM Length L Ch R = 1 ,12513   ,469.2,473.7,478.3
XS GIS Cut Line= 2
     2219182.379      362762.014     2218222.198      363586.412
#Sta/Elev= 30
       0 2196.83    70.3 2169.13   110.5  2158.5   180.8 2146.11   200.9 2141.66
   210.9 2136.82   261.1 2118.52   291.3 2113.75   321.4 2111.38   441.9 2106.47
   522.3 2107.32     693 2106.73   743.2 2108.06   783.4 2106.83   825.3  2104.2
   833.6 2103.59   840.3 2103.92   843.7 2104.09   863.8 2109.82     914 2112.24
     924 2114.44   954.2 2124.19  1044.6 2166.86  1094.8 2197.04  1104.8 2199.42
  1114.9 2203.18    1155 2228.48  1175.1 2244.22  1185.2 2250.03  1265.5 2289.78
#Mann= 3 , 0 , 0
       0      .1       0   825.3    .045       0   840.3      .1       0
Bank Sta=825.3,840.3
XS Rating Curve= 0 ,0
Exp/Cntr=0.3,0.1

Type RM Length L Ch R = 1 ,12039.3 ,326.7,328.5,330.3
XS GIS Cut Line= 3
     2218989.867      362657.635     2218355.507      363041.388
     2218135.409      363504.663
#Sta/Elev= 30
       0 2169.55      20 2161.39    40.1 2150.53   100.2 2130.16   130.2 2117.34
   150.3 2111.94   310.6  2104.6   400.8 2102.28   435.2 2102.53   450.2  2103.8
     501 2107.76   661.2 2107.56   791.7 2112.44   821.9 2111.48     842 2113.46
   922.4  2113.2   972.7 2118.22  1043.1  2133.3  1053.2  2137.8  1083.3 2164.43
  1093.4 2171.25  1123.6 2186.26  1133.6 2190.26  1143.7 2188.95  1183.9 2209.02
    1194 2212.76  1214.1 2217.27  1224.1 2222.24  1244.2 2226.25  1254.3 2224.68
#Mann= 3 , 0 , 0
       0      .1       0   435.2    .045       0   450.2      .1       0
Bank Sta=435.2,450.2
XS Rating Curve= 0 ,0
Exp/Cntr=0.3,0.1

Type RM Length L Ch R = 1 ,11710.7 ,436.3,433,429.2
XS GIS Cut Line= 3
     2218857.208      362409.617     2217969.011      362851.857
     2217523.055      363093.417
#Sta/Elev= 30
       0 2184.82      20 2174.99    30.1 2167.01    40.1 2161.81   100.2  2137.4
   110.2 2131.02   170.4 2111.55   200.4 2107.64   370.8 2100.34   383.3 2101.59
   398.3 2102.81   691.5 2104.16   972.2 2112.06    1022 2113.96  1041.9  2116.5
  1071.8 2125.44  1081.7 2131.02  1091.6 2134.26  1161.3 2154.89    1211  2175.5
  1240.8 2189.91  1260.7  2204.5  1300.5 2228.25  1330.3 2247.95  1350.2 2266.97
  1399.9 2299.82  1429.8 2322.75  1439.7 2335.04  1459.6 2345.14  1499.4 2356.15
#Mann= 3 , 0 , 0
       0      .1       0   383.3    .045       0   398.3      .1       0
Bank Sta=383.3,398.3
XS Rating Curve= 0 ,0
Exp/Cntr=0.3,0.1

Type RM Length L Ch R = 1 ,11277.7 ,544.4,535.1,526.3
XS GIS Cut Line= 3
     2218481.861      362145.759     2217894.685      362550.836
     2217485.256      362952.321
#Sta/Elev= 30
       0 2151.02      10 2144.72    40.2 2131.32    80.4 2115.66    90.4 2113.53
   110.5 2110.41   261.2  2104.7   328.5 2099.77   331.6 2099.66   343.5 2100.09
   371.7 2101.97   512.4 2101.17   592.8 2103.66   693.2 2104.88     824 2110.35
   884.4 2110.11   894.4 2111.78   924.6 2120.76   934.7 2124.86   974.9 2146.32
     995 2154.95  1005.1 2160.35  1045.3 2187.05  1115.8 2227.59  1135.9 2244.79
    1156 2253.32  1206.3  2284.6  1226.4 2297.37  1246.5 2313.61  1286.8 2338.69
#Mann= 3 , 0 , 0
       0      .1       0   328.5    .045       0   343.5      .1       0
Bank Sta=328.5,343.5
XS Rating Curve= 0 ,0
Exp/Cntr=0.3,0.1

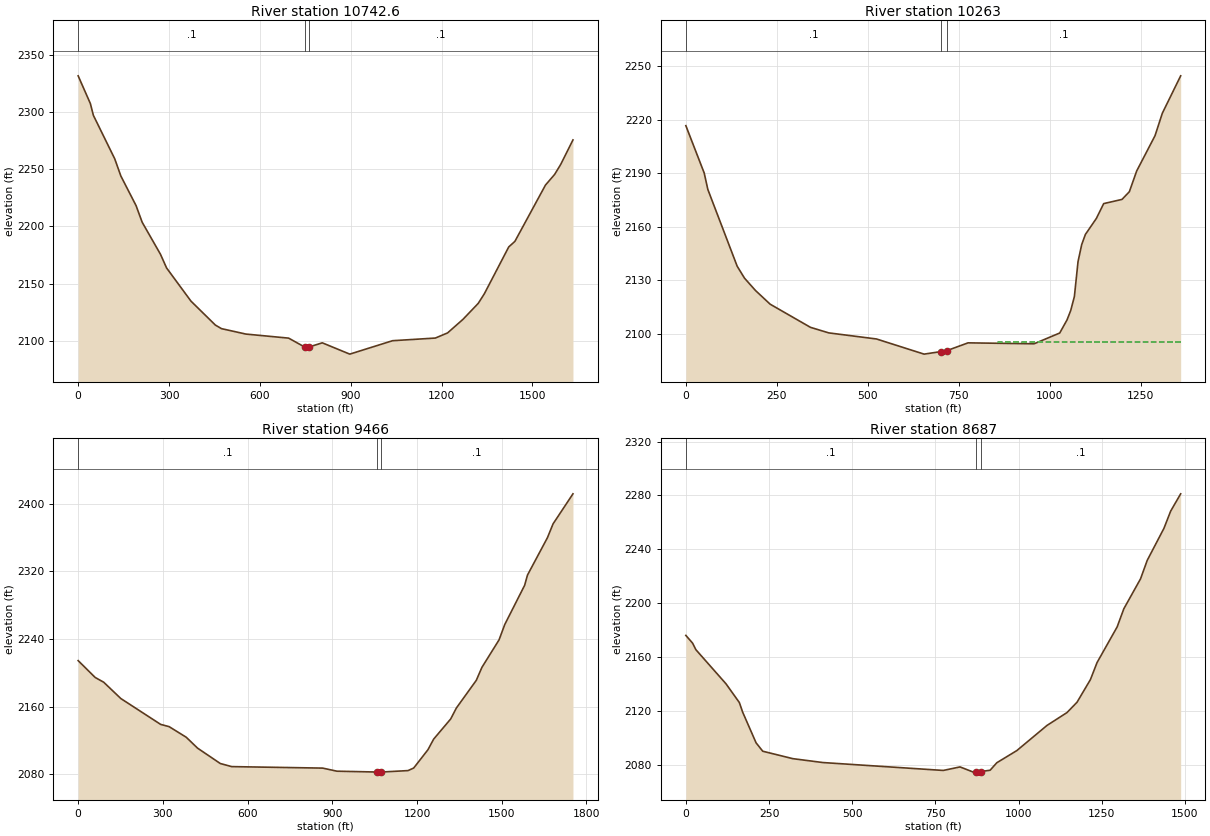
Type RM Length L Ch R = 1 ,10742.6 ,461.4,479.6,497.8
XS GIS Cut Line= 3
     2218484.065       361738.79     2217906.986      361879.423
     2217320.209      362737.767
#Sta/Elev= 30
       0 2331.53    40.3 2307.31    50.3    2297   120.8 2259.02   140.9 2244.06
   191.3 2218.08   211.4  2203.6   271.8 2175.63     292 2163.66   372.5 2134.69
     453 2113.79   473.2 2110.66   553.7 2105.92   694.9 2102.38   748.6  2094.5
   763.6 2094.75     806 2098.27   896.8  2088.4  1038.1 2100.12  1179.4 2102.44
  1219.8 2106.94  1270.3 2118.73  1320.8 2132.69    1341 2141.07  1421.7 2182.07
  1441.9 2186.88  1542.9 2236.08  1573.1 2245.37  1593.3 2254.17  1633.7 2275.54
#Mann= 3 , 0 , 0
       0      .1       0   748.6    .045       0   763.6      .1       0
Bank Sta=748.6,763.6
XS Rating Curve= 0 ,0
Exp/Cntr=0.3,0.1

Type RM Length L Ch R = 1 ,10263   ,802.1,796.9,791.7
XS GIS Cut Line= 2
     2218212.499      361539.965     2216874.064      361777.585
#Sta/Elev= 30
       0 2216.58    50.4 2190.09    60.4  2180.9     141 2137.95   161.1 2131.28
   191.3 2124.36   231.6 2116.71   342.4 2103.75   392.7 2100.65   523.6 2097.25
   654.5 2088.77   701.1  2090.2   716.1 2090.66   775.3 2095.08   956.6 2094.55
  1027.1 2100.58  1047.2 2107.92  1057.3 2113.17  1067.4 2120.98  1077.4 2140.52
  1087.5 2150.06  1097.6 2155.72  1127.8  2164.7  1147.9 2172.98  1198.2 2175.33
  1218.4 2179.63  1238.5 2191.21  1288.9 2210.96    1309 2223.54  1359.4 2244.47
#Mann= 3 , 0 , 0
       0      .1       0   701.1    .045       0   716.1      .1       0
#XS Ineff= 2 , 0
                          856.85         2095.58
Permanent Ineff=
       F       F
Bank Sta=701.1,716.1
XS Rating Curve= 0 ,0
Exp/Cntr=0.3,0.1

Type RM Length L Ch R = 1 ,9466    ,769.3,779,788.6
XS GIS Cut Line= 2
     2218357.981      360502.193     2216752.829      361205.356
#Sta/Elev= 30
       0  2214.4    60.4 2194.41    90.6 2188.76   151.1 2169.48   292.1 2138.84
   322.3 2136.13   382.7 2123.63     423 2110.66   503.6 2092.44   543.8 2088.81
   866.1 2087.03   916.5 2083.37  1057.5  2082.4  1067.6 2082.27  1072.5 2082.35
  1168.3 2084.08  1188.4 2087.16  1238.8  2108.8  1258.9 2121.32  1319.4 2145.29
  1339.5 2158.24    1410 2191.03  1430.1 2206.48  1490.6 2238.97  1510.7 2257.09
  1581.2 2303.61  1591.3 2315.74  1661.8  2359.9  1681.9 2376.42  1752.4 2412.02
#Mann= 3 , 0 , 0
       0      .1       0  1057.5    .045       0  1072.5      .1       0
Bank Sta=1057.5,1072.5
XS Rating Curve= 0 ,0
Exp/Cntr=0.3,0.1

Type RM Length L Ch R = 1 ,8687    ,643.6,642.7,641.8
XS GIS Cut Line= 2
     2218132.024       360173.03     2216645.064      360185.634
#Sta/Elev= 30
       0 2176.06    20.1 2170.36    30.1 2165.47   120.6 2140.14   160.8 2126.21
   170.8 2119.03     211 2096.32   231.1 2090.07   321.5 2084.56   411.9 2081.67
   773.6 2075.81   823.9 2078.43   864.1 2074.56   871.1  2074.7   886.1 2074.98
   914.3 2075.96   934.4 2081.51   994.7 2090.57  1085.1 2109.19  1145.4 2118.78
  1175.5 2126.44  1215.7 2143.22  1235.8 2155.94  1296.1 2182.37  1316.2 2195.84
  1366.4 2218.07  1386.5 2231.79  1436.8 2255.59  1456.9 2268.32    1487 2281.17
#Mann= 3 , 0 , 0
       0      .1       0   871.1    .045       0   886.1      .1       0
Bank Sta=871.1,886.1
XS Rating Curve= 0 ,0
Exp/Cntr=0.3,0.1