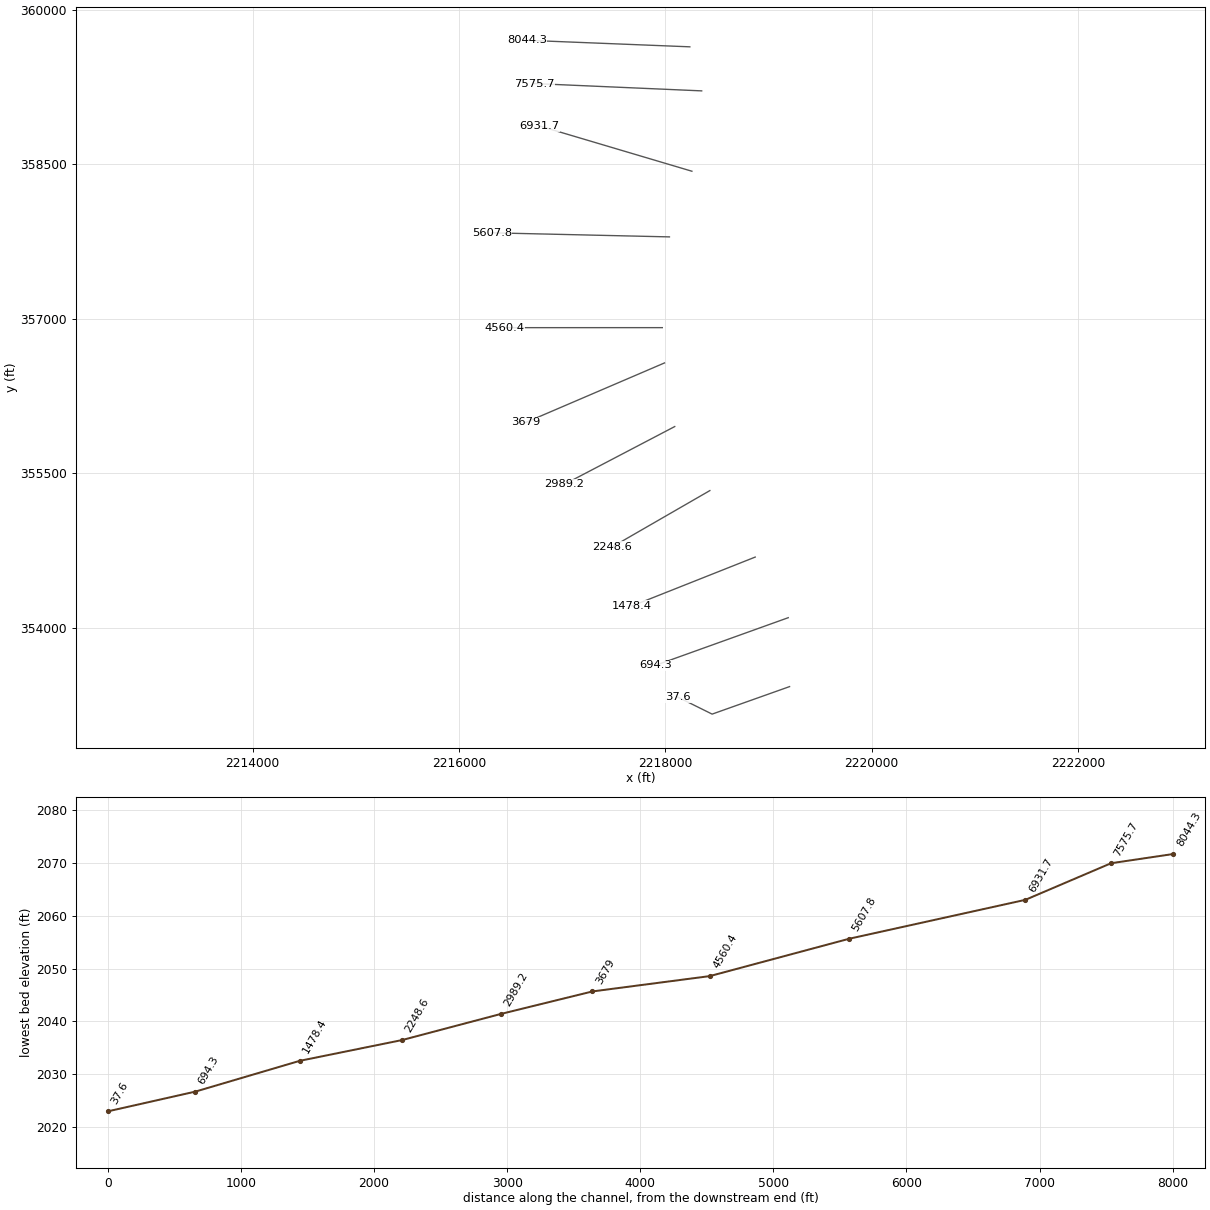
HEC-RAS study NFrkAntCk.prj: NFrkAntCk

--- NFrkAntCk.g01 (geometry) --- (continued)

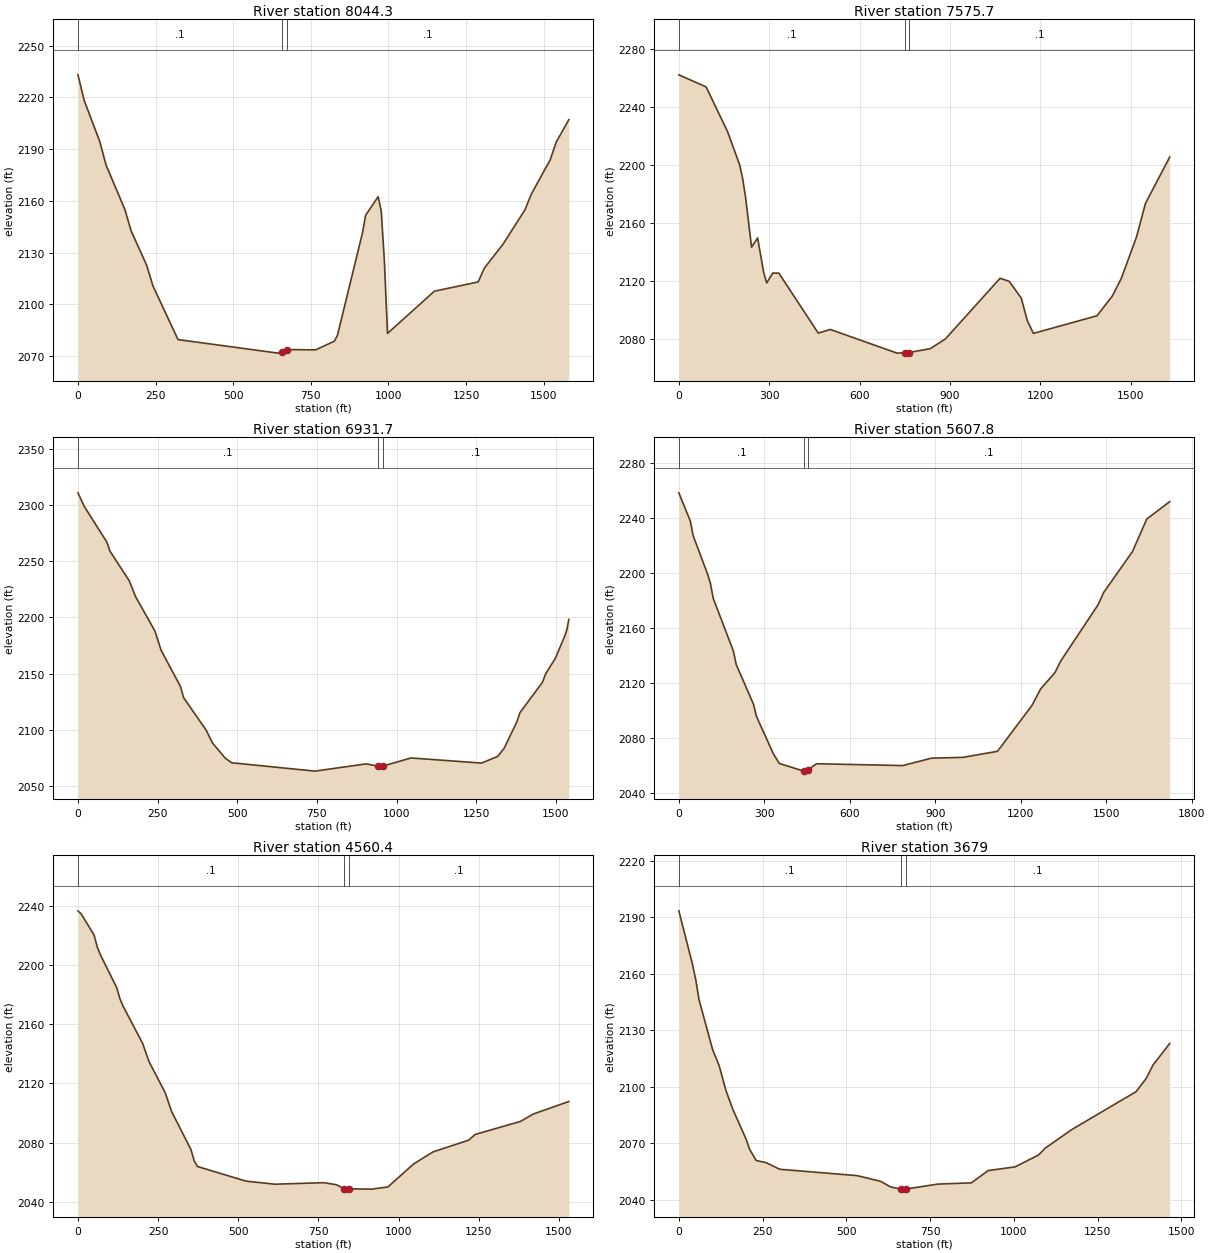
Type RM Length L Ch R = 1 ,8044.3  ,461.3,468.5,475.7
XS GIS Cut Line= 2
     2218238.938      359638.458     2216658.983      359701.815
#Sta/Elev= 30
       0 2233.04    20.1 2218.19    70.5 2194.25    90.6 2180.68   151.1 2154.98
   171.2 2142.59   221.6 2122.49   241.7 2110.57   322.3 2079.53   644.6 2071.68
     658  2072.2     673 2073.74   765.4 2073.57   825.9 2078.61   835.9    2082
   916.5 2141.39   926.6 2151.59   966.9 2162.36   976.9 2154.15     987 2125.35
   997.1 2083.12  1148.2  2107.6  1289.2 2112.95  1309.3 2121.02  1369.7 2134.96
  1440.2 2154.87  1460.4 2163.89  1520.8 2183.62  1540.9 2194.16  1581.2 2207.02
#Mann= 3 , 0 , 0
       0      .1       0     658    .045       0     673      .1       0
Bank Sta=658,673
XS Rating Curve= 0 ,0
Exp/Cntr=0.3,0.1

Type RM Length L Ch R = 1 ,7575.7  ,654.8,644.5,634.2
XS GIS Cut Line= 2
     2218353.772      359210.801     2216726.299      359282.077
#Sta/Elev= 30
       0 2262.34    90.5 2253.98   160.9 2223.42   201.1 2200.52   211.2 2191.28
   221.2 2178.05   241.3 2143.18   261.4 2149.59   281.6 2125.58   291.6 2118.43
   311.7  2125.3   331.8 2125.26   462.6 2083.78   502.8 2086.28     724 2069.93
   749.1 2070.13   764.1 2070.36   834.6 2073.03   884.9 2079.81  1065.9 2121.65
  1096.1  2119.6  1136.3 2107.98  1156.4 2092.38  1176.5 2083.57  1387.7 2095.76
    1438 2109.22  1468.1 2121.51  1518.4 2149.99  1548.6 2173.52    1629 2205.49
#Mann= 3 , 0 , 0
       0      .1       0   749.1    .045       0   764.1      .1       0
Bank Sta=749.1,764.1
XS Rating Curve= 0 ,0
Exp/Cntr=0.3,0.1

Type RM Length L Ch R = 1 ,6931.7  ,1317,1323.3,1329.4
XS GIS Cut Line= 3
     2218258.737      358430.723     2216793.616        358866.3
     2216781.736       358870.26
#Sta/Elev= 30
       0 2311.14    20.1 2298.86    90.5 2267.34   100.6  2259.1   160.9 2232.76
     181 2218.52   241.3 2188.08   261.4 2170.52   321.8  2138.5   331.8 2128.41
   402.2 2099.69   422.4 2088.06   462.6 2074.49   482.7 2070.44   744.1    2063
     905 2069.47   942.1 2067.43   957.1  2067.5  1045.8 2074.74    1267 2070.17
  1317.3  2076.1  1337.4 2083.12  1377.7 2106.75  1387.7 2115.21  1458.1  2142.2
  1468.2 2149.72  1498.3  2163.4  1528.5 2183.64  1534.8 2189.06    1541 2198.24
#Mann= 3 , 0 , 0
       0      .1       0   942.1    .045       0   957.1      .1       0
Bank Sta=942.1,957.1
XS Rating Curve= 0 ,0
Exp/Cntr=0.3,0.1

Type RM Length L Ch R = 1 ,5607.8  ,1047.1,1047.5,1047.8
XS GIS Cut Line= 2
     2218040.949      357793.197     2216318.441      357832.795
#Sta/Elev= 30
       0 2258.02    40.3 2237.48    50.4 2226.76   100.8  2198.9   110.8 2192.15
   120.9 2181.13   191.4 2142.97   201.5  2133.1     262  2104.3     272 2095.79
   282.1 2090.99   332.5 2067.94   352.6 2061.22   438.5 2055.66   443.3 2055.64
   453.5 2056.68   483.6 2061.02   785.9 2059.68   886.7 2065.06   997.5 2065.66
  1118.4 2070.05  1239.3 2103.35  1269.6 2115.34  1319.9  2127.2  1340.1 2135.62
  1471.1 2176.49  1491.2 2185.57    1592 2215.23  1642.4 2238.96    1723 2251.62
#Mann= 3 , 0 , 0
       0      .1       0   438.5    .045       0   453.5      .1       0
Bank Sta=438.5,453.5
XS Rating Curve= 0 ,0
Exp/Cntr=0.3,0.1

Type RM Length L Ch R = 1 ,4560.4  ,862.6,881.3,896.3
XS GIS Cut Line= 2
      2217971.86      356912.166     2216440.587      356911.991
#Sta/Elev= 30
       0 2236.66    10.1  2234.6    50.4 2220.25    60.4 2212.07    70.5 2206.69
   120.9 2184.76     131 2177.18     141 2172.11   201.5 2147.23   221.6  2134.8
     272  2113.8   292.2 2100.99   352.6 2075.26   362.7 2067.68   372.7 2063.87
   523.9 2053.99   614.5  2051.9   765.6 2052.92   805.9 2051.58   830.5 2048.75
   845.5 2048.75   916.8 2048.57   967.1 2050.07  1047.7 2065.68  1108.2 2073.78
    1219 2081.66  1239.1 2085.54  1380.2 2094.31  1420.5 2099.33  1531.3  2107.8
#Mann= 3 , 0 , 0
       0      .1       0   830.5    .045       0   845.5      .1       0
Bank Sta=830.5,845.5
XS Rating Curve= 0 ,0
Exp/Cntr=0.3,0.1

Type RM Length L Ch R = 1 ,3679    ,697.6,689.8,685.8
XS GIS Cut Line= 2
     2217993.431      356569.623     2216647.104      355991.494
#Sta/Elev= 30
       0 2193.37    40.1 2165.41    50.2 2157.07    60.2 2146.25   100.4 2119.94
   120.4 2111.15   140.5 2098.05   160.6 2088.25   200.7 2072.19   210.8 2066.97
   230.8 2060.88   260.9 2059.68   301.1 2056.21   531.9 2052.84   602.1 2049.82
   632.2 2046.82   662.1 2045.71   672.4 2045.67   677.1  2045.7   772.8 2048.34
   873.1    2049   923.3 2055.52  1003.6 2057.48  1073.8  2063.8  1093.9 2067.48
  1174.2 2077.43  1364.8 2097.39    1395 2104.42    1415 2111.42  1465.2 2122.98
#Mann= 3 , 0 , 0
       0      .1       0   662.1    .045       0   677.1      .1       0
Bank Sta=662.1,677.1
XS Rating Curve= 0 ,0
Exp/Cntr=0.3,0.1

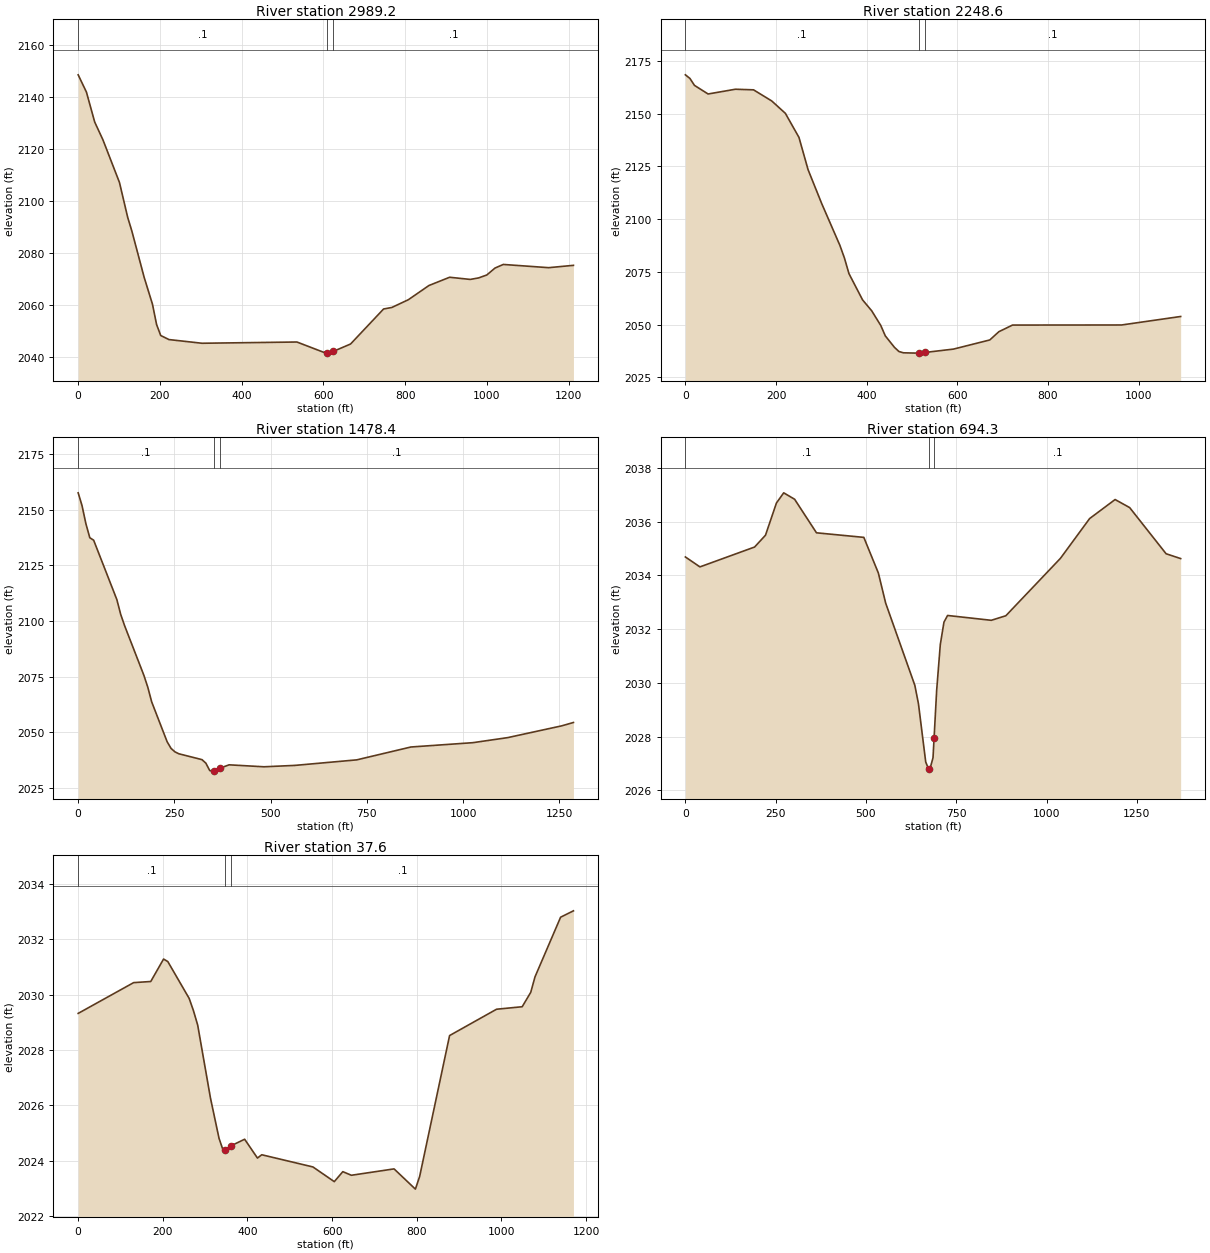
Type RM Length L Ch R = 1 ,2989.2  ,740.5,740.3,740.2
XS GIS Cut Line= 2
     2218092.426      355951.896     2217019.324      355389.606
#Sta/Elev= 30
       0 2148.55    20.2  2141.9    40.4 2130.38    60.6 2123.51     101 2107.11
   121.2 2093.63   131.2 2088.46   161.5 2070.53   181.7 2060.25   191.8 2052.42
   201.9 2048.18   222.1 2046.62   302.9  2045.2   535.1 2045.68   605.8  2041.4
   609.1 2041.51   624.1 2042.07   666.3 2044.91   747.1  2058.4   767.3 2058.98
   807.7 2061.97   858.1 2067.44   908.6 2070.61   959.1 2069.78   979.3 2070.35
   999.5 2071.48  1019.7 2074.16  1039.9 2075.54  1150.9  2074.3  1211.5  2075.2
#Mann= 3 , 0 , 0
       0      .1       0   609.1    .045       0   624.1      .1       0
Bank Sta=609.1,624.1
XS Rating Curve= 0 ,0
Exp/Cntr=0.3,0.1

Type RM Length L Ch R = 1 ,2248.6  ,772.4,770.4,768.3
XS GIS Cut Line= 2
     2218432.968      355330.209     2217486.579      354783.759
#Sta/Elev= 30
       0 2168.48      10 2166.77      20 2163.48    50.1 2159.39   110.3 2161.64
   150.4 2161.36   190.5 2156.09   220.6 2150.22   250.6 2138.81   270.7  2123.5
   300.8  2107.4   340.9  2087.6   350.9 2081.61   360.9  2074.2     391 2061.71
   411.1 2056.55   431.1  2049.6   441.1 2044.66   461.2 2039.24   471.2 2037.23
   481.2 2036.62   511.3 2036.47   514.4 2036.53   529.4 2036.81   591.5 2038.38
   671.7 2042.72   691.8 2046.65   721.9 2049.78   962.5 2049.82  1092.8 2053.85
#Mann= 3 , 0 , 0
       0      .1       0   514.4    .045       0   529.4      .1       0
Bank Sta=514.4,529.4
XS Rating Curve= 0 ,0
Exp/Cntr=0.3,0.1

Type RM Length L Ch R = 1 ,1478.4  ,784.1,783.8,783.5
XS GIS Cut Line= 2
     2218872.504      354684.764     2217676.648       354209.59
#Sta/Elev= 30
       0 2157.55      10 2151.81    20.1 2143.64    30.2 2137.38    40.2 2136.27
   100.5 2109.58   110.6 2102.87   120.6 2097.88   170.9 2075.49     181 2070.15
     191 2063.63   231.2  2045.7   241.3 2042.74   251.3  2041.2   261.4 2040.33
   321.7 2037.69   331.8  2036.1   341.8 2032.78   351.9 2032.53   352.6 2032.58
   367.6 2033.78   392.1 2035.36   482.6 2034.48     563  2035.1   723.8 2037.59
   864.6 2043.37  1025.4 2045.31  1115.9 2047.58  1256.6 2052.88  1286.8 2054.38
#Mann= 3 , 0 , 0
       0      .1       0   352.6    .045       0   367.6      .1       0
Bank Sta=352.6,367.6
XS Rating Curve= 0 ,0
Exp/Cntr=0.3,0.1

Type RM Length L Ch R = 1 ,694.3   ,656.9,656.7,656.6
XS GIS Cut Line= 2
     2219192.821      354096.217     2217902.259      353632.328
#Sta/Elev= 30
       0 2034.69    40.3 2034.32   191.6 2035.06   221.8  2035.5   252.1  2036.7
   272.3 2037.08   302.5 2036.84     363 2035.59   494.1 2035.42   534.4 2034.09
   554.6 2032.97   635.3 2029.91   645.4 2029.22   665.5 2027.05   673.6 2026.78
   675.6 2026.71   685.7 2027.21   688.6 2027.93   695.8 2029.72   705.9 2031.43
     716 2032.26     726 2032.51     847 2032.33   887.4  2032.5  1038.6 2034.64
  1119.3 2036.12  1189.9 2036.83  1230.2 2036.53  1331.1 2034.81  1371.4 2034.63
#Mann= 3 , 0 , 0
       0      .1       0   673.6    .045       0   688.6      .1       0
Bank Sta=673.6,688.6
XS Rating Curve= 0 ,0
Exp/Cntr=0.3,0.1

Type RM Length L Ch R = 1 ,37.6    ,31.1,37.6,44.1
XS GIS Cut Line= 3
     2219205.703      353427.271     2218454.899      353160.131
     2218120.271      353326.039
#Sta/Elev= 30
       0 2029.32   131.1 2030.43   171.5 2030.47   201.8 2031.28   211.8 2031.19
   262.3 2029.86   272.4 2029.42   282.4  2028.9   312.7 2026.26   332.9 2024.81
     343 2024.36   347.1 2024.39   362.1 2024.55   393.4 2024.78   423.7  2024.1
   433.8 2024.22   554.8 2023.78   605.2 2023.25   625.4 2023.61   645.6 2023.48
   746.5 2023.71   796.9 2022.98     807 2023.44   877.7 2028.52   988.7 2029.47
  1049.3 2029.56  1069.5 2030.08  1079.6 2030.64  1140.1 2032.79  1170.4 2033.02
#Mann= 3 , 0 , 0
       0      .1       0   347.1    .045       0   362.1      .1       0
Bank Sta=347.1,362.1
XS Rating Curve= 0 ,0
Exp/Cntr=0.3,0.1

Chan Stop Cuts=-1
Use User Specified Reach Order=0
Composite Channel Slope=5